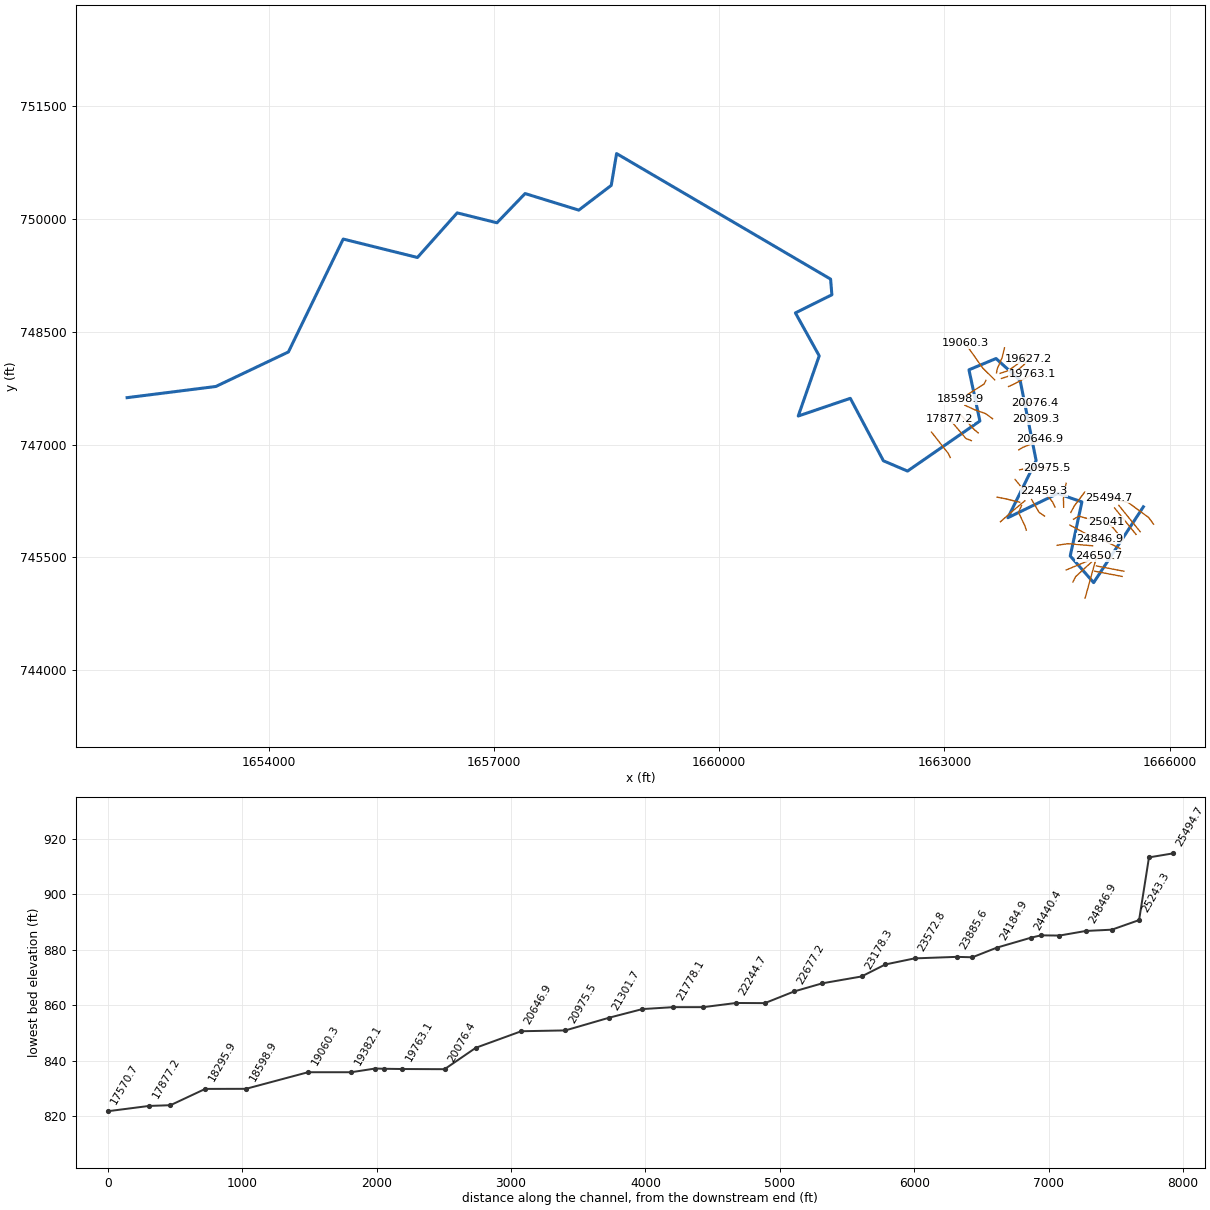
--- TOMLINRN.prj (project) ---

Proj Title=TOMLINRN
Current Plan=p01
Default Exp/Contr=0,0
English Units
Geom File=g01
Flow File=f01
Plan File=p01
BEGIN DESCRIPTION:
END DESCRIPTION:
DSS Export Rating Curves= 0
DSS Export Rating Curve Sorted= 0
DSS Export Volume Flow Curves= 0
DXF Filename=..\..\..\..\..\Engineering\Hydraulics\TOMLINRN\TOMLINRN.
DXF OffsetX= 0
DXF OffsetY= 0
DXF ScaleX= 0
DXF ScaleY= 0

--- TOMLINRN.p01 (plan) ---

Plan Title=Floodplain
Program Version=4.10
Geom File=g01
Flow File=f01
Subcritical Flow
K Sum by GR= 0
Std Step Tol= 0.01
Critical Tol= 0.01
Num of Std Step Trials= 20
Max Error Tol= 0.3
Flow Tol Ratio= 0.001
Split Flow NTrial= 30
Split Flow Tol= 0.02
Split Flow Ratio= 0.02
Log Output Level= 0
Friction Slope Method= 1
Unsteady Friction Slope Method= 2
Unsteady Bridges Friction Slope Method= 1
Parabolic Critical Depth
Global Vel Dist= 0 , 0 , 0
Global Log Level= 0
CheckData=True
Encroach Param=-1 ,0,0, 0
Run HTab= 0
Run UNet= 0
Run PostProcess= 0
Run WQNet= 0
UNET Theta= 0
UNET Theta Warmup= 0
UNET ZTol= 0
UNET ZSATol= 0
UNET MxIter= 0
UNET MaxInSteps= 0
UNET DtIC= 0
UNET DtMin= 0
UNET MaxCRTS= 0
UNET WFStab= 0
UNET SFStab= 0
UNET WFX= 1
UNET SFX= 1
UNET DSS MLevel= 1
UNET DZMax Abort= 0
UNET Convert EG Bridges= 0
UNET Use Existing IB Tables= 0
UNET Froude Reduction=False
UNET Froude Limit= 0
UNET Froude Power= 0
UNET Time Slicing=0,0, 5
UNET Junction Losses=0
Write IC File= 0
Write IC File at Sim End=0
Echo Input=False
Echo Parameters=False
Echo Output=False
Write Detailed= 0
WQ AD Non Conservative
WQ ULTIMATE=-1
WQ Max Comp Step=1HOUR
WQ Output Interval=15MIN
WQ Output Selected Increments= 0
WQ Output face flow=0
WQ Output face velocity=0
WQ Output face area=0
WQ Output face dispersion=0
WQ Output cell volume=0
WQ Output cell surface area=0
WQ Output cell continuity=0
WQ Output cumulative cell continuity=0
WQ Output face conc=0
WQ Output face dconc_dx=0
WQ Output face courant=0
WQ Output face peclet=0
WQ Output face adv mass=0
WQ Output face disp mass=0
WQ Output cell mass=0
WQ Output cell source sink temp=0
WQ Output cell source sink nsm=0
WQ Output MaxMinRange=-1
WQ Daily Max Min Mean=-1
WQ Daily Range=0
WQ Daily Time=0
WQ Create Restart=0
WQ Fixed Restart=0
WQ System Summary=0
WQ Use Fixed Temperature=0
Sorting and Armoring Iterations= 10
XS Update Threshold= 0.02
Hydraulics Update Threshold= 0.02
Energy Slope Method= 1
Volume Change Method= 0
XS Weighting Method= 0
Number of US Weighted Cross Sections= 1
Number of DS Weighted Cross Sections= 1
Upstream XS Weight=0.25
Main XS Weight=0.5
Downstream XS Weight=0.25
Number of DS XS's Weighted with US Boundary= 1
Upstream Boundary Weight= 1
Weight of XSs Associated with US Boundary= 0
Number of US XS's Weighted with DS Boundary= 1
Downstream Boundary Weight= 0.5
Weight of XSs Associated with DS Boundary= 0.5
Sediment Output Level= 4
Mass or Volume Output= 0
Output Increment Type= 1
Profile and TS Output Increment= 10
XS Output Flag= 0
XS Output Increment= 10
Disregard all LS=0
Disregard all Conn=0
Disregard all Breaches=0
Disregard all Pumps=0

--- TOMLINRN.f01 (steady flow) ---

Flow Title=NFF Regression Equation
Program Version=4.10
Number of Profiles= 1
Profile Names=P100yr
River Rch & RM=TOMLINRN,Main            ,25494.7
4385.418
River Rch & RM=TOMLINRN,Main            ,11460.1
4633.398
River Rch & RM=TOMLINRN,Main            ,8762.5
5141.399
Boundary for River Rch & Prof#=TOMLINRN,Main            , 1
Up Type= 0
Dn Type= 1
Dn Known WS=695.1
DSS Import GetInterval= 0
DSS Import GetPeak= 0
DSS Import FillOption= 0

--- TOMLINRN.g01 (geometry) ---

Geom Title=2003 WVU SAMB 3 Meter DEM
Program Version=4.10

River Reach=TOMLINRN        ,Main
Reach XY= 30
     1665648.248      746172.356     1664986.179      745163.703
     1664674.342       745518.61     1664829.821        746237.7
     1664507.797       746349.82     1663844.686      746027.419
     1664220.047      746788.727     1664007.446      747854.676
     1663686.265      748145.474     1663326.022      747995.735
     1663471.422      747314.311      1662507.88      746648.078
     1662186.699      746784.797     1661746.161       747615.96
     1661052.786      747380.302     1661332.153      748181.383
     1661015.177      748752.573     1661500.651      748993.681
     1661483.574      749202.332     1658634.151      750872.665
     1658563.172      750449.323      1658130.71      750120.301
     1657415.794      750340.559     1657041.166      749951.685
     1656511.786      750083.408     1655982.603      749490.054
     1654994.141      749735.264     1654264.695      748233.099
     1653298.281      747773.589     1652116.871      747624.792

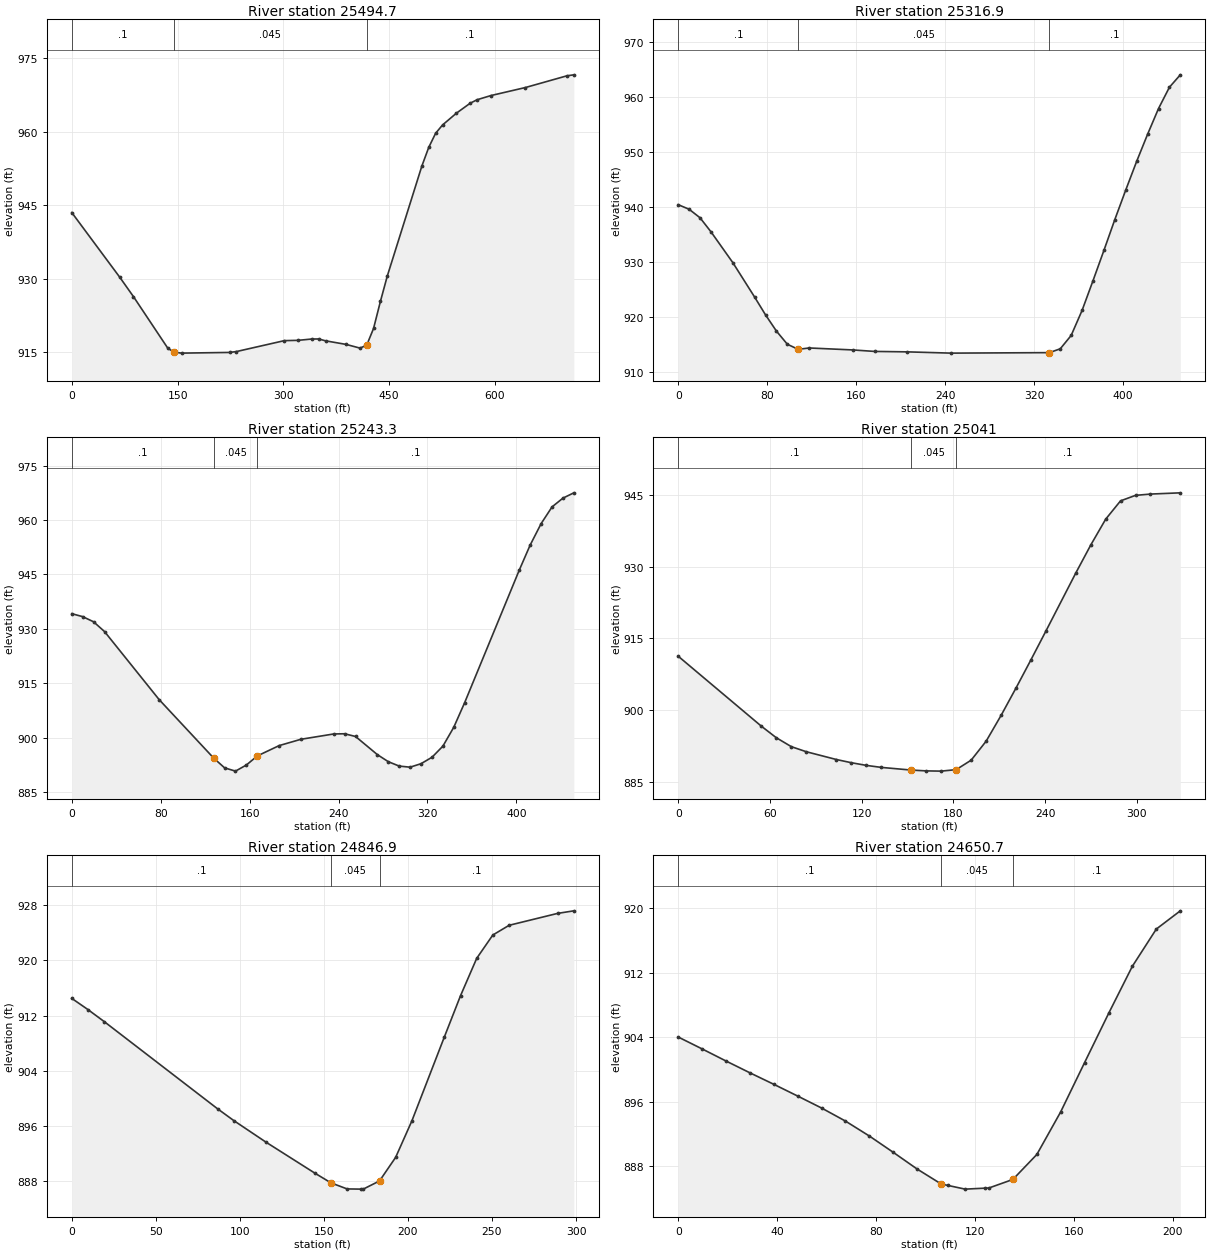
Type RM Length L Ch R = 1 ,25494.7 ,186.4,177.9,170.8
XS GIS Cut Line= 4
     1665783.401      745941.221     1665720.901      746028.026
     1665446.595      746229.415     1665189.651      746291.915
#Sta/Elev= 30
       0  943.49    68.1  930.27    87.5  926.32   136.1  915.81     145914.9836
   155.6   914.8   223.6  914.94   233.4  915.12   301.4  917.35   320.9  917.41
   340.3  917.68     350  917.69   359.8  917.31   388.9  916.58   408.4  915.83
     418916.3942   427.8  919.84   437.5  925.35   447.3  930.55   496.2  952.95
     506  956.78   515.8  959.67   525.6  961.36   545.2  963.76   564.8   965.8
   574.6  966.51   594.2  967.36   643.1     969   701.9  971.39   711.7  971.59
#Mann= 3 , 0 , 0
       0      .1       0     145    .045       0     418      .1       0
Bank Sta=145,418
XS Rating Curve= 0 ,0
Exp/Cntr=0.3,0.1

Type RM Length L Ch R = 1 ,25316.9 ,70.9,73.5,73.9
XS GIS Cut Line= 2
     1665605.883       745840.96     1665321.161      746191.655
#Sta/Elev= 28
       0   940.4     9.8  939.57    19.6  938.02    29.5  935.45    49.1  929.85
    68.7  923.58    78.6  920.31    88.4  917.36    98.2  914.97     108  914.05
   117.8   914.3   157.1  913.94   176.8  913.67   206.2  913.59   245.5  913.36
   333.9  913.45   343.7  914.15   353.5  916.58   363.3  921.13   373.2  926.58
     383  932.09   392.8   937.7   402.6  943.07   412.4  948.28   422.3  953.25
   432.1  957.92   441.9   961.8   451.7  964.06
#Mann= 3 , 0 , 0
       0      .1       0     108    .045       0   333.9      .1       0
Bank Sta=108,333.9
XS Rating Curve= 0 ,0
Exp/Cntr=0.3,0.1

Type RM Length L Ch R = 1 ,25243.3 ,202.4,202.3,202.1
XS GIS Cut Line= 2
     1665549.894      745805.804     1665265.172      746156.498
#Sta/Elev= 30
       0  934.18     9.8  933.37    19.6  931.95    29.5  929.24    78.6  910.47
   127.7  894.32   137.5  891.63   147.3  890.73   157.1  892.42   166.9  894.92
   186.6  897.78   206.2  899.52   235.7  900.99   245.5  901.04   255.3  900.29
     275  895.27   284.8  893.33   294.6  892.12   304.4  891.82   314.2  892.78
   324.1  894.56   333.9  897.63   343.7  902.85   353.5  909.65   402.6  946.21
   412.4  953.12   422.3  959.06   432.1  963.66   441.9  966.08   451.7  967.54
#Mann= 3 , 0 , 0
       0      .1       0   127.7    .045       0   166.9      .1       0
Bank Sta=127.7,166.9
XS Rating Curve= 0 ,0
Exp/Cntr=0.3,0.1

Type RM Length L Ch R = 1 ,25041   ,184.4,194.1,203.8
XS GIS Cut Line= 4
     1665373.679      745732.887     1665352.845      745760.665
     1665241.734      745897.818     1665151.456      745972.471
#Sta/Elev= 26
       0  911.28    54.3  896.68    64.1  894.26      74  892.38    83.8  891.32
   103.4   889.7   113.2  889.03     123  888.47   132.8  888.05   152.4  887.49
   162.2  887.32     172  887.27   181.8  887.58   191.6  889.56   201.4  893.53
   211.2  898.93     221  904.68   230.8  910.59   240.5  916.55     260  928.65
   269.8  934.51   279.6  939.93   289.3  943.75   299.1   944.9   308.9  945.17
   328.4  945.43
#Mann= 3 , 0 , 0
       0      .1       0   152.4    .045       0   181.8      .1       0
Bank Sta=152.4,181.8
XS Rating Curve= 0 ,0
Exp/Cntr=0.3,0.1

Type RM Length L Ch R = 1 ,24846.9 ,189.8,196.2,202.5
XS GIS Cut Line= 2
     1665338.956      745617.002     1665071.595      745750.248
#Sta/Elev= 21
       0  914.49     9.6  912.87    19.3  911.12    86.7  898.47    96.4  896.75
   115.6  893.61   144.5  889.14   154.2  887.71   163.8  886.83   172.2   886.8
   173.4   886.8   183.1  887.99   192.7  891.42   202.4  896.74   221.6  908.85
   231.3  914.89   240.9   920.3   250.5  923.69   260.2   925.1   289.1  926.83
   298.7   927.2
#Mann= 3 , 0 , 0
       0      .1       0   154.2    .045       0   183.1      .1       0
Bank Sta=154.2,183.1
XS Rating Curve= 0 ,0
Exp/Cntr=0.3,0.1

Type RM Length L Ch R = 1 ,24650.7 ,137.6,137.4,137.2
XS GIS Cut Line= 2
     1665259.095      745481.151     1665059.442       745517.61
#Sta/Elev= 24
       0     904     9.7  902.52    19.3  901.03      29  899.56    38.7  898.13
    48.3  896.68      58  895.19    67.6  893.58    77.3  891.72      87  889.69
    96.6  887.63   106.3  885.78     109   885.6     116  885.14     124  885.26
   125.6  885.28   135.3  886.34     145  889.44   154.6   894.7   164.3  900.83
     174  906.92   183.6  912.77   193.3  917.39     203  919.65
#Mann= 3 , 0 , 0
       0      .1       0   106.3    .045       0   135.3      .1       0
Bank Sta=106.3,135.3
XS Rating Curve= 0 ,0
Exp/Cntr=0.3,0.1

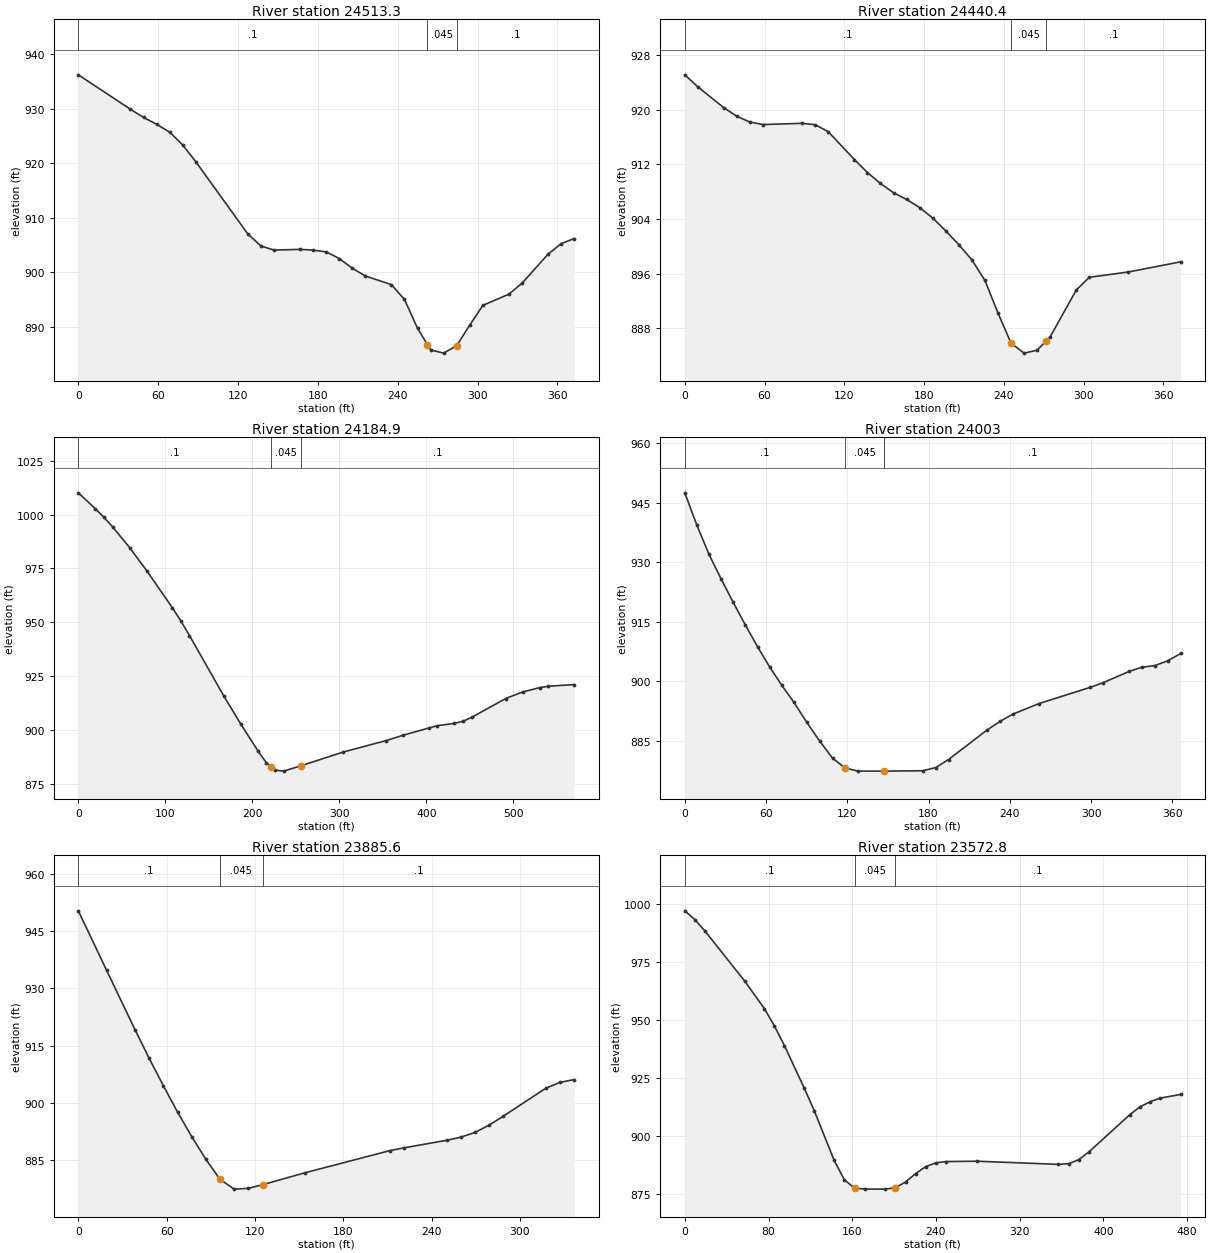
Type RM Length L Ch R = 1 ,24513.3 ,72.9,72.9,72.9
XS GIS Cut Line= 2
      1665388.87      745315.353     1665022.984      745385.665
#Sta/Elev= 30
       0  936.18    39.2  929.87      49  928.38    58.8  927.13    68.6   925.7
    78.4  923.35    88.2  920.29   127.5     907   137.3  904.83   147.1  904.09
   166.7  904.22   176.5  904.08   186.3  903.76   196.1  902.54   205.9  900.76
   215.7  899.35   235.3  897.76   245.1  895.04   254.9  889.77   262.3  886.79
   264.7  885.82   274.5  885.22   284.3  886.58   294.1  890.34     304  893.97
   323.6  896.02   333.4  898.01     353  903.34   362.8  905.26   372.6   906.2
#Mann= 3 , 0 , 0
       0      .1       0   262.3    .045       0   284.3      .1       0
Bank Sta=262.3,284.3
XS Rating Curve= 0 ,0
Exp/Cntr=0.3,0.1

Type RM Length L Ch R = 1 ,24440.4 ,293,255.4,217.9
XS GIS Cut Line= 2
     1665364.998      745245.908     1664998.679      745316.221
#Sta/Elev= 30
       0  925.09     9.8  923.34    29.4  920.27    39.3  919.01    49.1  918.18
    58.9  917.82    88.3     918    98.2  917.79     108  916.76   127.6   912.7
   137.4   910.8   147.2   909.2   157.1  907.84   166.9  906.86   176.7  905.68
   186.5  904.14   196.3  902.28   206.1  900.26     216  898.02   225.8  895.02
   235.6  890.25   245.4  885.86   255.2  884.39     265  884.82   271.7  886.14
   274.8  886.75   294.5  893.62   304.3  895.48   333.7  896.26     373  897.74
#Mann= 3 , 0 , 0
       0      .1       0   245.4    .045       0   271.7      .1       0
Bank Sta=245.4,271.7
XS Rating Curve= 0 ,0
Exp/Cntr=0.3,0.1

Type RM Length L Ch R = 1 ,24184.9 ,194.5,182,169.3
XS GIS Cut Line= 2
     1664872.376       744957.28      1665024.72      745506.325
#Sta/Elev= 30
       0 1010.12    19.6  1002.7    29.5  998.71    39.3  994.36    58.9   984.7
    78.6  973.92   108.1  956.68   117.9  950.52   127.7  943.81     167  915.84
   186.6  902.71   206.3  890.26   216.1  884.66   221.8  882.71     226  881.27
   235.8  880.78   255.4   883.2   304.5  889.67   353.7  894.96   373.3  897.47
   402.8  900.82   412.6  901.91   432.2  902.96   442.1  903.98   451.9  905.75
   491.2  914.53   510.8   917.6   530.5  919.62   540.3  920.23   569.8  921.02
#Mann= 3 , 0 , 0
       0      .1       0   221.8    .045       0   255.4      .1       0
Bank Sta=221.8,255.4
XS Rating Curve= 0 ,0
Exp/Cntr=0.3,0.1

Type RM Length L Ch R = 1 ,24003   ,125.2,117.4,109.4
XS GIS Cut Line= 3
     1664709.616      745172.123     1664746.508      745243.738
     1664957.012       745436.88
#Sta/Elev= 30
       0  947.46       9  939.24    17.9  931.92    26.8  925.78    35.8  919.82
    44.8   914.1    53.7  908.68    62.7  903.55    71.6  898.95    80.6  894.65
    90.1   889.6    99.6  884.89   109.1  880.57   118.6  878.05   128.2   877.3
   147.2   877.3   175.8   877.4   185.3  878.19   194.8  880.23   223.4   887.7
   232.9  889.85   242.4  891.68   261.5  894.32   299.6  898.44   309.1  899.61
   328.2  902.44   337.7   903.5   347.2  903.91   356.7  905.12   366.2  906.96
#Mann= 3 , 0 , 0
       0      .1       0   118.6    .045       0   147.2      .1       0
Bank Sta=118.6,147.2
XS Rating Curve= 0 ,0
Exp/Cntr=0.3,0.1

Type RM Length L Ch R = 1 ,23885.6 ,323.7,312.8,302
XS GIS Cut Line= 2
     1664620.206      745331.846      1664930.97      745462.054
#Sta/Elev= 23
       0  950.29    19.2  934.73    38.5   919.2    48.1  911.71    57.8   904.5
    67.4  897.63      77  891.22    86.6  885.28    96.3     880   105.9  877.45
   115.4  877.65   125.2  878.61     154  881.73   211.8  887.54   221.4  888.27
   250.3  890.23   259.9  891.05   269.6   892.3   279.2  894.22   288.8  896.55
   317.7  903.87   327.3  905.39   336.9  906.13
#Mann= 3 , 0 , 0
       0      .1       0    96.3    .045       0   125.2      .1       0
Bank Sta=96.3,125.2
XS Rating Curve= 0 ,0
Exp/Cntr=0.3,0.1

Type RM Length L Ch R = 1 ,23572.8 ,227,217.8,208.5
XS GIS Cut Line= 3
     1664501.283      745660.405     1664642.342      745682.106
     1664972.203      745653.894
#Sta/Elev= 30
       0  997.22     9.5  993.47      19  988.64    57.1  966.93    76.1  954.91
    85.6  947.48    95.2  938.96   114.2  920.52   123.7  910.82   142.7  889.36
   152.5  880.89   162.2  877.36   171.9   876.9   191.4  876.93   201.1  877.48
   210.9  879.96   220.6  883.64   230.4  886.67   240.1  888.29   249.8  888.82
     279  888.98   356.9  887.61   366.7  887.89   376.4  889.63   386.2     893
   425.1  909.04   434.8  912.42   444.6  914.68   454.3  916.25   473.8  917.84
#Mann= 3 , 0 , 0
       0      .1       0   162.2    .045       0   201.1      .1       0
Bank Sta=162.2,201.1
XS Rating Curve= 0 ,0
Exp/Cntr=0.3,0.1

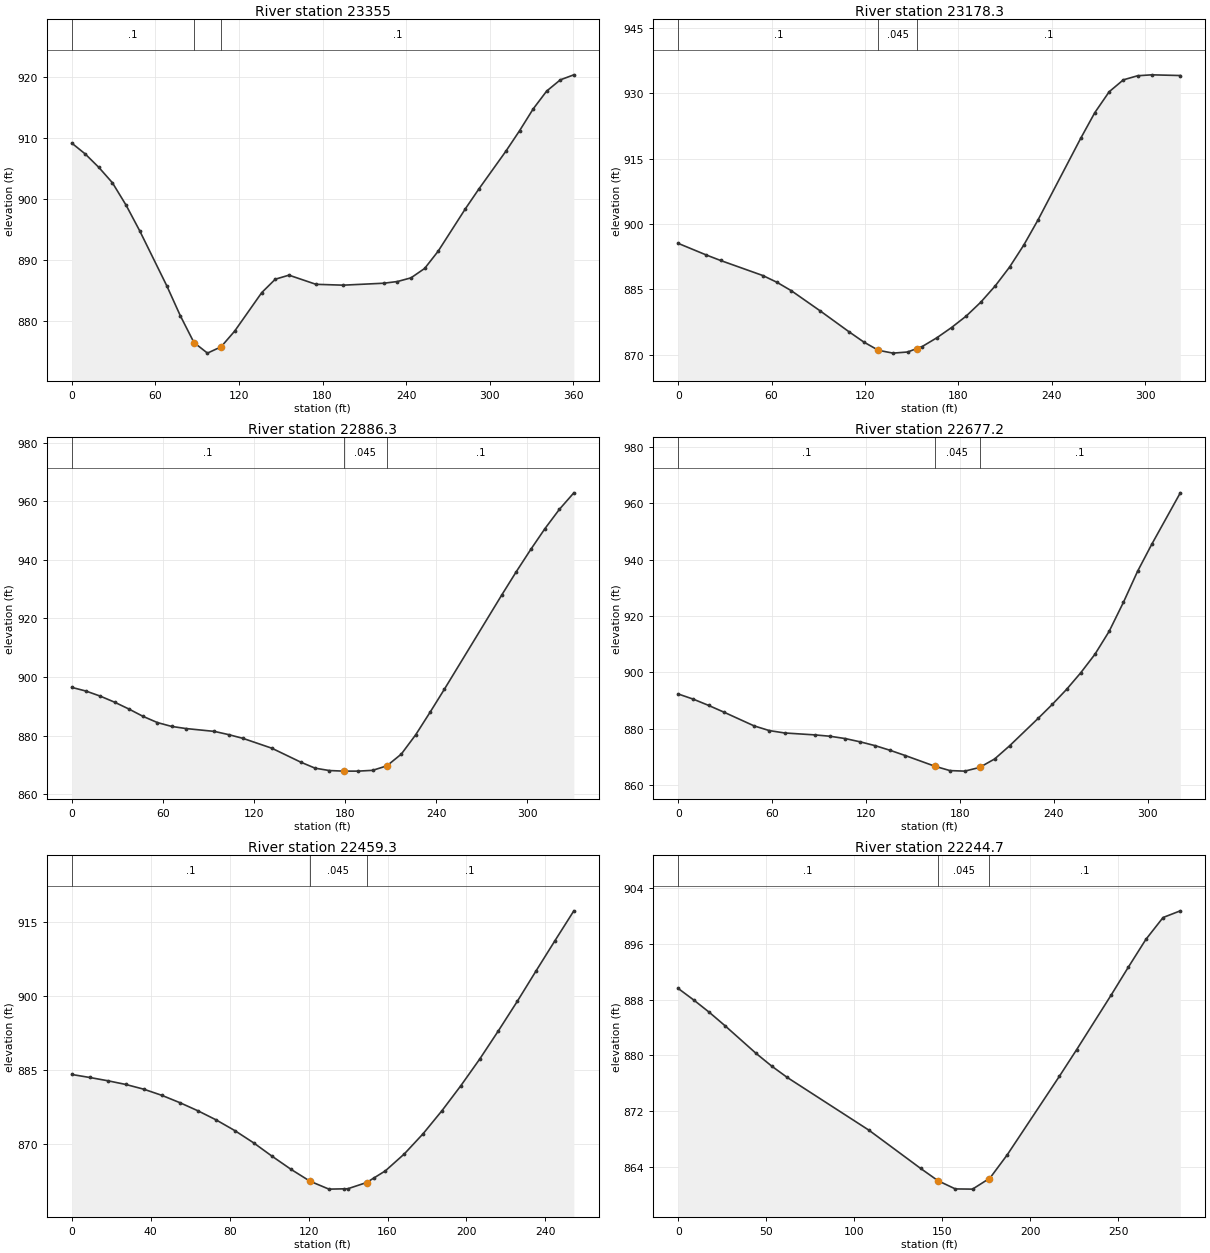
Type RM Length L Ch R = 1 ,23355   ,169.9,176.6,183.2
XS GIS Cut Line= 2
      1664670.12      745929.068     1664987.394      745758.061
#Sta/Elev= 30
       0  909.13     9.7  907.34    19.5  905.13    29.2  902.62      39  898.95
    48.7  894.78    68.2  885.74    77.9  880.84    87.7  876.44    97.4   874.7
   107.2  875.74   116.9   878.3   136.4  884.63   146.1  886.82   155.9  887.48
   175.3  885.98   194.8  885.84     224  886.16   233.8  886.44   243.5  887.04
   253.3  888.58     263  891.41   282.5  898.35   292.2   901.6   311.7  907.83
   321.5  911.18   331.2  914.73   340.9  917.66   350.7   919.5   360.4  920.32
#Mann= 3 , 0 , 0
       0      .1       0    87.7    .045       0   107.2      .1       0
Bank Sta=87.7,107.2
XS Rating Curve= 0 ,0
Exp/Cntr=0.3,0.1

Type RM Length L Ch R = 1 ,23178.3 ,266.3,292,317.6
XS GIS Cut Line= 4
     1664717.429      746007.193     1664788.609      746047.123
     1664906.665      746015.873      1665024.72      746001.985
#Sta/Elev= 29
       0  895.54    18.1  892.87    27.2  891.62    54.4  888.16    63.5   886.6
    72.6   884.7      91  880.11   109.8  875.25   119.2  872.92   128.6  871.02
     138  870.37   147.4  870.63   153.2  871.41   156.8  871.89   166.2   873.9
   175.6  876.24     185  878.86   194.3  882.02   203.7   885.8   212.9  890.11
     222  895.14   231.2  900.94   258.6  919.64   267.7  925.55   276.9  930.32
     286  933.05   295.2  933.99   304.3   934.2   322.6  934.04
#Mann= 3 , 0 , 0
       0      .1       0   128.6    .045       0   153.2      .1       0
Bank Sta=128.6,153.2
XS Rating Curve= 0 ,0
Exp/Cntr=0.3,0.1

Type RM Length L Ch R = 1 ,22886.3 ,198.7,209.1,219.6
XS GIS Cut Line= 3
     1664682.706      746097.471     1664726.109      746180.804
      1664868.47       746370.04
#Sta/Elev= 30
       0  896.47     9.4  895.21    18.8  893.48    28.2  891.42    37.6   889.1
      47  886.57    56.4  884.47    65.8  883.15    75.2  882.43      94  881.45
   103.4  880.35   112.9  879.06   131.8  875.72   150.8  870.98   160.3  868.91
   169.7   868.1   179.2   867.9   188.7   867.9   198.2  868.17   207.6   869.7
   217.1   873.7   226.6   880.3     236  887.93   245.5  895.84   283.4  928.07
   292.9  935.96   302.4  943.52   311.8  950.66   321.3  957.23   330.8  962.84
#Mann= 3 , 0 , 0
       0      .1       0   179.2    .045       0   207.6      .1       0
Bank Sta=179.2,207.6
XS Rating Curve= 0 ,0
Exp/Cntr=0.3,0.1

Type RM Length L Ch R = 1 ,22677.2 ,198.3,217.9,237.6
XS GIS Cut Line= 4
      1664587.22      746166.915     1664583.748      746283.235
     1664601.109      746376.985      1664618.47      746484.623
#Sta/Elev= 30
       0  892.33     9.7  890.48    19.4  888.28    29.1  885.91    48.5  881.01
    58.2  879.35    67.9  878.51    87.3  877.82      97  877.34   106.7  876.52
   116.4  875.34   125.9  873.99   135.4  872.35     145  870.51     164   866.7
   173.6  865.16   183.1  864.97   192.6  866.29   202.2   869.3   211.7  873.94
   229.9  883.65     239  888.64   248.1  893.95   257.1   899.8   266.2  906.38
   275.3  914.53   284.4  924.79   293.5  935.86   302.6  945.48   320.8  963.68
#Mann= 3 , 0 , 0
       0      .1       0     164    .045       0   192.6      .1       0
Bank Sta=164,192.6
XS Rating Curve= 0 ,0
Exp/Cntr=0.3,0.1

Type RM Length L Ch R = 1 ,22459.3 ,218.1,214.6,211.1
XS GIS Cut Line= 3
     1664470.901      746170.387     1664439.651       746236.36
     1664325.067      746376.985
#Sta/Elev= 30
       0  884.03     9.1  883.42    18.2  882.76    27.4     882    36.5  881.04
    45.6   879.8    54.8   878.3    63.9  876.66      73  874.84    82.6  872.64
    92.1  870.16   101.6   867.4   111.2  864.74   120.7  862.36   130.3  860.75
     138  860.81   139.8  860.82   149.4  862.09     153  862.99   158.9  864.46
   168.5   867.9     178  871.99   187.6  876.69   197.1  881.73   206.7  887.16
   216.2  892.92   225.8  898.92   235.3  905.09   244.8  911.18   254.4  917.26
#Mann= 3 , 0 , 0
       0      .1       0   120.7    .045       0   149.4      .1       0
Bank Sta=120.7,149.4
XS Rating Curve= 0 ,0
Exp/Cntr=0.3,0.1

Type RM Length L Ch R = 1 ,22244.7 ,245,243.3,241.4
XS GIS Cut Line= 3
     1664332.012       746048.86     1664259.095      746099.207
     1664160.137      746269.346
#Sta/Elev= 22
       0  889.61     8.9  887.94    17.7  886.18    26.6  884.26    44.3  880.28
    53.2  878.45      62  876.83   108.3  869.28   137.8  863.77   147.7     862
   157.5  860.83   167.3   860.8   176.6  862.29   177.2  862.39     187  865.72
   216.6  876.98   226.4   880.8   246.1  888.67   255.9  892.69   265.8  896.65
   275.6   899.8   285.4  900.76
#Mann= 3 , 0 , 0
       0      .1       0   147.7    .045       0   176.6      .1       0
Bank Sta=147.7,176.6
XS Rating Curve= 0 ,0
Exp/Cntr=0.3,0.1

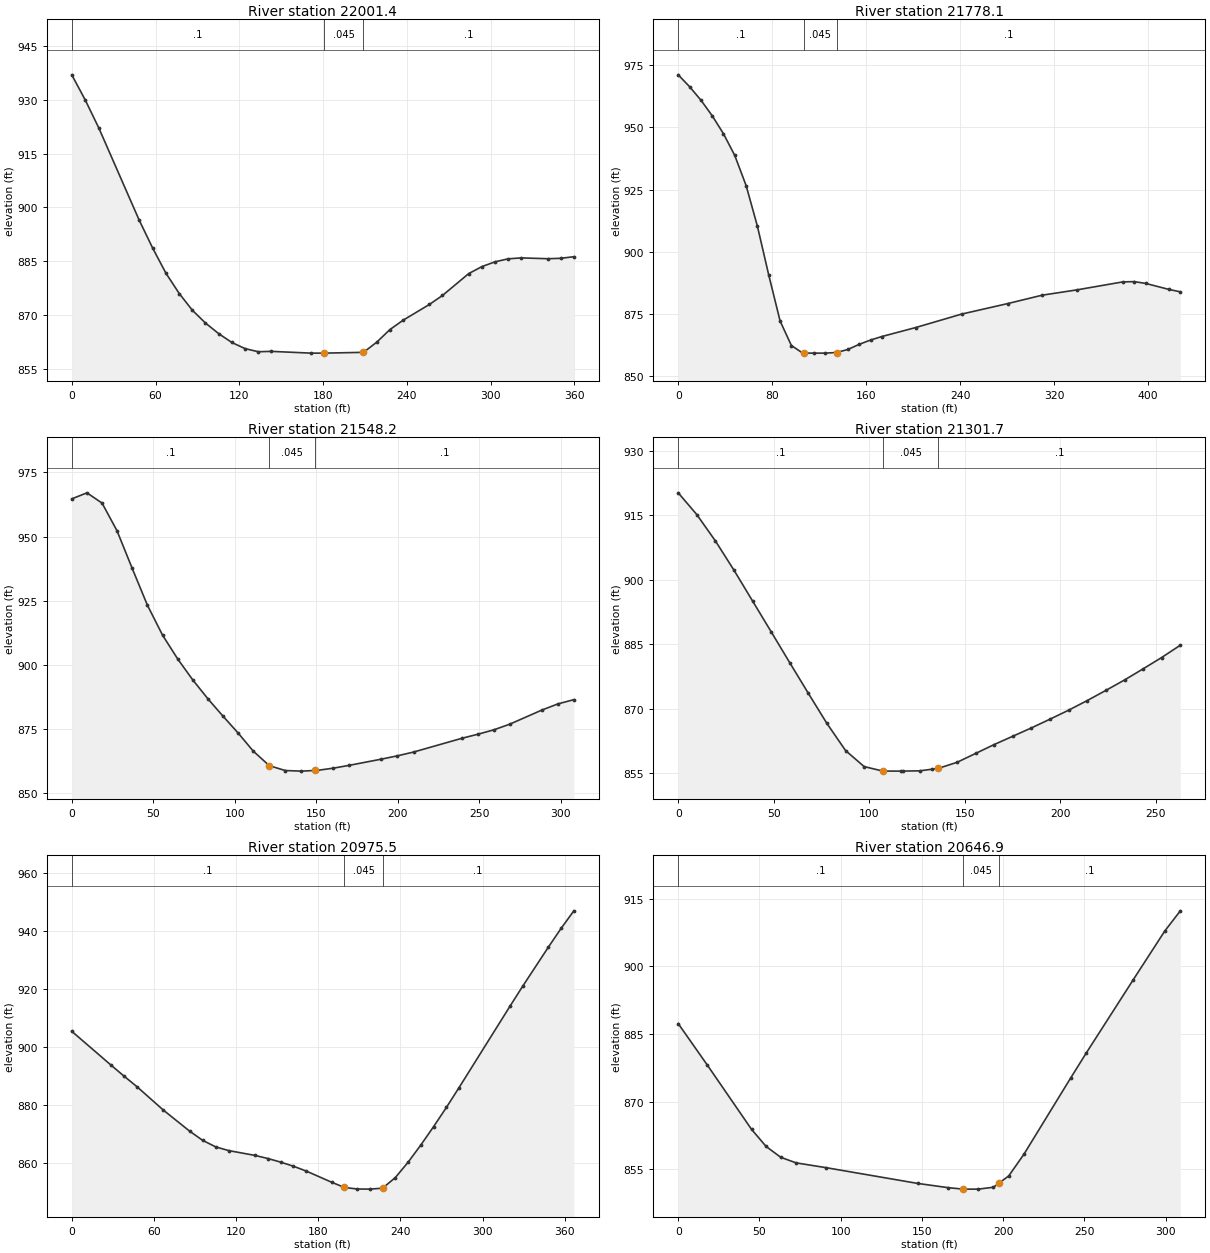
Type RM Length L Ch R = 1 ,22001.4 ,253.2,223.3,193.3
XS GIS Cut Line= 4
     1664088.956       745861.36     1664068.123      745925.596
     1663986.526      746095.735     1664026.456      746191.221
#Sta/Elev= 30
       0  937.03     9.6  930.04    19.3  922.25    48.2  896.53    57.9  888.68
    67.5   881.6      77  875.95    86.4  871.27    95.8   867.7   105.3  864.73
   114.7  862.27   124.1  860.57   133.6  859.69     143  859.79   171.3   859.3
   180.8   859.3     209  859.52   218.5  862.36   227.9  865.87   237.4   868.5
   256.2  872.89   265.6  875.41   284.4  881.52   293.9  883.48   303.3  884.81
   312.7  885.64   322.1   885.9   340.9  885.67   350.3  885.78   359.7  886.23
#Mann= 3 , 0 , 0
       0      .1       0   180.8    .045       0     209      .1       0
Bank Sta=180.8,209
XS Rating Curve= 0 ,0
Exp/Cntr=0.3,0.1

Type RM Length L Ch R = 1 ,21778.1 ,251.1,229.9,208.6
XS GIS Cut Line= 3
     1663745.206      745974.207     1663911.873       746120.04
     1664069.859      746251.985
#Sta/Elev= 30
       0  971.08     9.6  966.34    19.3  960.91    28.9  954.65    38.5  947.42
    48.1  938.71    57.8  926.57    67.4  910.24      77  890.72    86.7  872.19
    96.3  862.36   105.9  859.32   106.7  859.32   115.6   859.3   125.2   859.3
   134.8  859.55   144.4  860.77   154.1  862.85   163.7  864.56   173.3  865.97
   202.2  869.59   241.1  874.97   280.3  879.19   309.7  882.57   339.1  884.69
   378.3  887.91   388.1  888.02   397.9  887.29   417.5   884.9   427.3  883.92
#Mann= 3 , 0 , 0
       0      .1       0   106.7    .045       0   134.8      .1       0
Bank Sta=106.7,134.8
XS Rating Curve= 0 ,0
Exp/Cntr=0.3,0.1

Type RM Length L Ch R = 1 ,21548.2 ,261.7,246.5,231.5
XS GIS Cut Line= 3
     1663701.804      746300.596     1663811.179      746279.762
     1664002.151      746232.887
#Sta/Elev= 30
       0  964.71     9.3  967.07    18.6  963.06    27.8  952.21    37.1  937.58
    46.4  923.28    55.7  911.59      65   902.3    74.2  894.18    83.5   886.8
    92.8     880   102.1  873.42   111.3  866.42   121.2  860.72     131  858.83
   140.8   858.6   149.3  858.86   150.7   858.9   160.5  859.76   170.3  860.87
     190  863.28   199.8  864.57   209.7  866.04   239.2  871.38     249  872.96
   258.8  874.67   268.6  876.88   288.3  882.38   298.2   884.8     308  886.46
#Mann= 3 , 0 , 0
       0      .1       0   121.2    .045       0   149.3      .1       0
Bank Sta=121.2,149.3
XS Rating Curve= 0 ,0
Exp/Cntr=0.3,0.1

Type RM Length L Ch R = 1 ,21301.7 ,304.7,326.2,347.7
XS GIS Cut Line= 2
     1663939.651      746536.707     1664106.317      746333.582
#Sta/Elev= 30
       0  920.23     9.7  915.18    19.5  909.01    29.2  902.22    38.9  895.08
    48.7  887.87    58.4   880.7    68.1   873.6    77.8  866.61    87.6  860.28
    97.3  856.56     107  855.52   116.8   855.5   117.7  855.51   126.5  855.57
   132.7  855.94   136.2  856.15     146  857.56   155.7  859.62   165.4  861.69
   175.2  863.63   184.9  865.56   194.6  867.59   204.4  869.69   214.1  871.92
   223.8  874.27   233.6   876.7   243.3  879.28     253  881.92   262.8  884.78
#Mann= 3 , 0 , 0
       0      .1       0     107    .045       0   136.2      .1       0
Bank Sta=107,136.2
XS Rating Curve= 0 ,0
Exp/Cntr=0.3,0.1

Type RM Length L Ch R = 1 ,20975.5 ,321.4,328.6,335.9
XS GIS Cut Line= 4
     1664000.415      746665.179     1664132.359      746687.748
     1664262.567      746694.693     1664364.998      746692.957
#Sta/Elev= 30
       0  905.39    28.7   893.7    38.2   889.9    47.8  886.19    66.9  878.18
      86  870.95    95.6  867.74   105.2  865.47   114.7   864.2   133.9  862.53
   143.2  861.47   152.5  860.24   161.8  858.82   171.1  857.17   189.7   853.3
   199.1  851.48   208.4  850.95   217.7   850.9     227  851.23   236.3  854.88
   245.6  860.16   254.9   866.1   264.2  872.43   273.6  879.09   282.9  885.98
   320.1  914.08   329.4     921   348.1  934.45   357.4  940.93   366.7  946.98
#Mann= 3 , 0 , 0
       0      .1       0   199.1    .045       0     227      .1       0
Bank Sta=199.1,227
XS Rating Curve= 0 ,0
Exp/Cntr=0.3,0.1

Type RM Length L Ch R = 1 ,20646.9 ,344.1,337.5,330.7
XS GIS Cut Line= 4
     1663989.998      746930.804     1664043.817       746963.79
     1664182.706      747019.346     1664262.567      747073.165
#Sta/Elev= 20
       0  887.32      18  878.07    45.1  863.87    54.1  860.06    63.1  857.66
    72.5  856.43    91.2  855.35   147.3  851.87     166  850.93   175.3   850.6
   184.7   850.6     194  851.02   197.3   851.9   203.4  853.53   212.7  858.31
   241.6   875.3   251.2  880.85   280.1  897.09   299.4  907.84     309  912.34
#Mann= 3 , 0 , 0
       0      .1       0   175.3    .045       0   197.3      .1       0
Bank Sta=175.3,197.3
XS Rating Curve= 0 ,0
Exp/Cntr=0.3,0.1

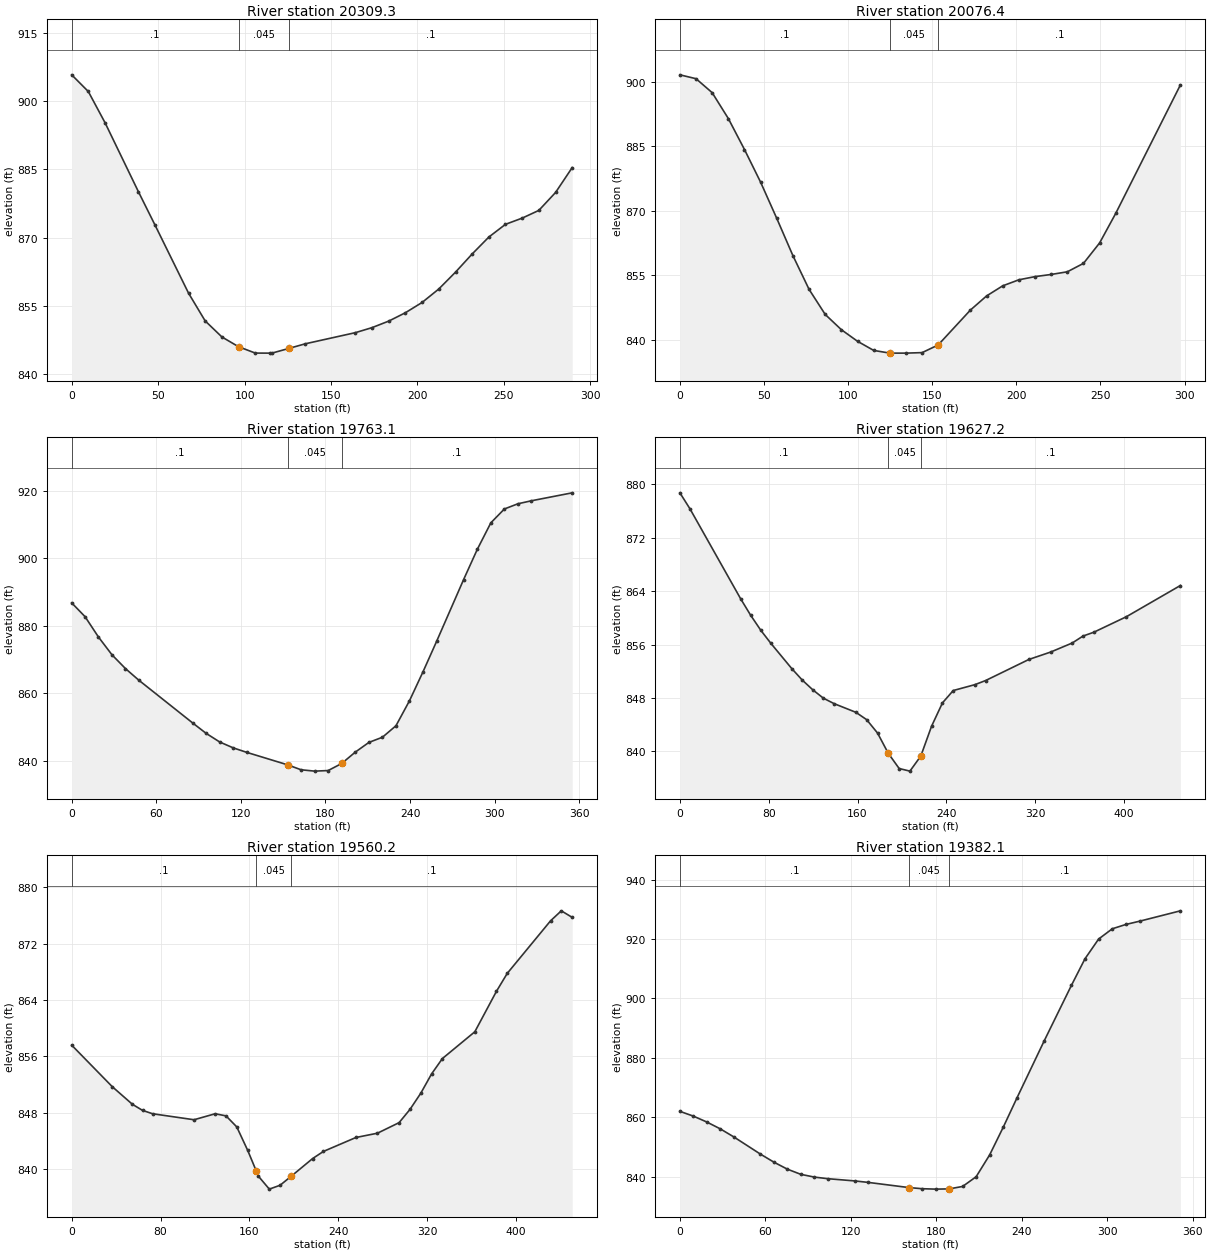
Type RM Length L Ch R = 1 ,20309.3 ,233.9,232.9,233
XS GIS Cut Line= 2
      1663922.29      747309.276     1664210.484      747337.054
#Sta/Elev= 28
       0  905.79     9.6  902.13    19.3  895.26    38.6   880.1    48.3   872.7
    67.6  857.81    77.2  851.72    86.9  848.19    96.5  846.05   106.2  844.65
   114.7  844.64   115.8  844.64   125.5  845.66   135.1  846.69   164.1  849.14
   173.7  850.24   183.4  851.68     193  853.51   202.7  855.78   212.3  858.72
     222  862.43   231.6  866.41   241.3  870.15   250.9  872.94   260.6  874.31
   270.2     876   279.9  879.95   289.5  885.41
#Mann= 3 , 0 , 0
       0      .1       0    96.5    .045       0   125.5      .1       0
Bank Sta=96.5,125.5
XS Rating Curve= 0 ,0
Exp/Cntr=0.3,0.1

Type RM Length L Ch R = 1 ,20076.4 ,303.4,313.3,322.1
XS GIS Cut Line= 2
     1663904.929      747538.443     1664201.804       747557.54
#Sta/Elev= 28
       0  901.57     9.6  900.67    19.2  897.42    28.8  891.41    38.4  884.21
      48  876.61    57.6   868.2    67.2  859.54    76.8  851.71    86.4  845.88
      96  842.34   105.6  839.65   115.2  837.53   124.8   836.9   134.4   836.9
     144  837.02   153.5  838.79   172.7  846.91   182.3  850.19   191.9  852.54
   201.5  853.94   211.1  854.68   220.7  855.18   230.3   855.8   239.9  857.76
   249.5  862.51   259.1   869.4   297.5  899.22
#Mann= 3 , 0 , 0
       0      .1       0   124.8    .045       0   153.5      .1       0
Bank Sta=124.8,153.5
XS Rating Curve= 0 ,0
Exp/Cntr=0.3,0.1

Type RM Length L Ch R = 1 ,19763.1 ,132.6,135.9,139.1
XS GIS Cut Line= 3
     1663852.845      747772.818      1663922.29      747804.068
     1664168.817      747934.276
#Sta/Elev= 30
       0  886.77     9.5  882.67      19  876.65    28.6  871.38    38.1  867.33
    47.6  863.88    85.8  851.22    95.4  848.13     105  845.58   114.6  843.84
   124.2  842.51   153.1  838.83   162.7  837.36   172.3  836.96   181.9  837.13
   191.5  839.22   201.1  842.57   210.8  845.46   220.4  846.99     230  850.39
   239.6   857.8   249.2  866.38   258.8  875.35     278  893.68   287.7  902.62
   297.3  910.46   306.9  914.56   316.5   916.1   326.1  916.99     355  919.34
#Mann= 3 , 0 , 0
       0      .1       0   153.1    .045       0   191.5      .1       0
Bank Sta=153.1,191.5
XS Rating Curve= 0 ,0
Exp/Cntr=0.3,0.1

Type RM Length L Ch R = 1 ,19627.2 ,67.3,67,67
XS GIS Cut Line= 6
     1663759.095      747880.457     1663845.901      747908.235
     1663880.623       747923.86     1663983.054      747998.512
     1664064.651      748067.957     1664113.262      748140.873
#Sta/Elev= 30
       0  878.73     9.1  876.33    54.7  862.87    63.8  860.38    72.9  858.14
      82  856.18   100.7  852.42   110.2  850.69   119.7  849.23   129.2  847.98
     139  847.15   158.5  845.86   168.2  844.76     178  842.76   187.7  839.72
   197.5  837.44   207.2  837.05     217  839.31   226.7  843.78   236.5  847.27
   246.2  849.12   265.7     850   275.4  850.62   314.4  853.78   333.9  854.88
   353.4  856.24   363.1  857.28   372.8  857.85   402.1  860.17   450.8  864.85
#Mann= 3 , 0 , 0
       0      .1       0   187.7    .045       0     217      .1       0
Bank Sta=187.7,217
XS Rating Curve= 0 ,0
Exp/Cntr=0.3,0.1

Type RM Length L Ch R = 1 ,19560.2 ,165.8,178.2,190.2
XS GIS Cut Line= 6
     1663739.998      747948.165     1663826.804      747975.943
     1663861.526      747991.568     1663963.956      748066.221
     1664045.554      748135.665     1664094.165      748208.582
#Sta/Elev= 30
       0  857.58    36.5  851.69    54.7  849.18    63.8  848.32    72.9  847.84
   110.2  846.99   129.2  847.84     139  847.54   148.7  845.97   158.5  842.65
   166.1  839.77   168.2  838.97     178  837.14   187.7  837.69   197.5  838.94
     217  841.48   226.7  842.49     256  844.47   275.4  845.08   294.9  846.58
   304.7  848.46   314.4  850.75   324.2  853.51   333.9  855.68   363.1  859.48
   382.6  865.23   392.3  867.77   431.3  875.23     441  876.65   450.8  875.72
#Mann= 3 , 0 , 0
       0      .1       0   166.1    .045       0   197.5      .1       0
Bank Sta=166.1,197.5
XS Rating Curve= 0 ,0
Exp/Cntr=0.3,0.1

Type RM Length L Ch R = 1 ,19382.1 ,298.4,321.8,345.1
XS GIS Cut Line= 4
     1663693.123       747955.11      1663703.54      748010.665
     1663767.776      748158.235     1663799.026      748288.443
#Sta/Elev= 30
       0  861.98     9.4  860.38    18.8  858.41    28.3   856.1    37.7  853.42
    56.5   847.6      66  844.88    75.5  842.51    84.9  840.78    94.4  839.85
   103.9  839.31   122.8  838.56   132.3  838.06   160.7  836.33   170.1  835.94
   179.6   835.8   189.1  835.88   198.5   836.7     208  839.97   217.5  847.33
     227  856.61   236.6  866.44   255.7  885.62   274.9  904.38   284.4  913.31
     294  919.97   303.6  923.42   313.1  924.87   322.7  925.96   351.4  929.46
#Mann= 3 , 0 , 0
       0      .1       0   160.7    .045       0   189.1      .1       0
Bank Sta=160.7,189.1
XS Rating Curve= 0 ,0
Exp/Cntr=0.3,0.1

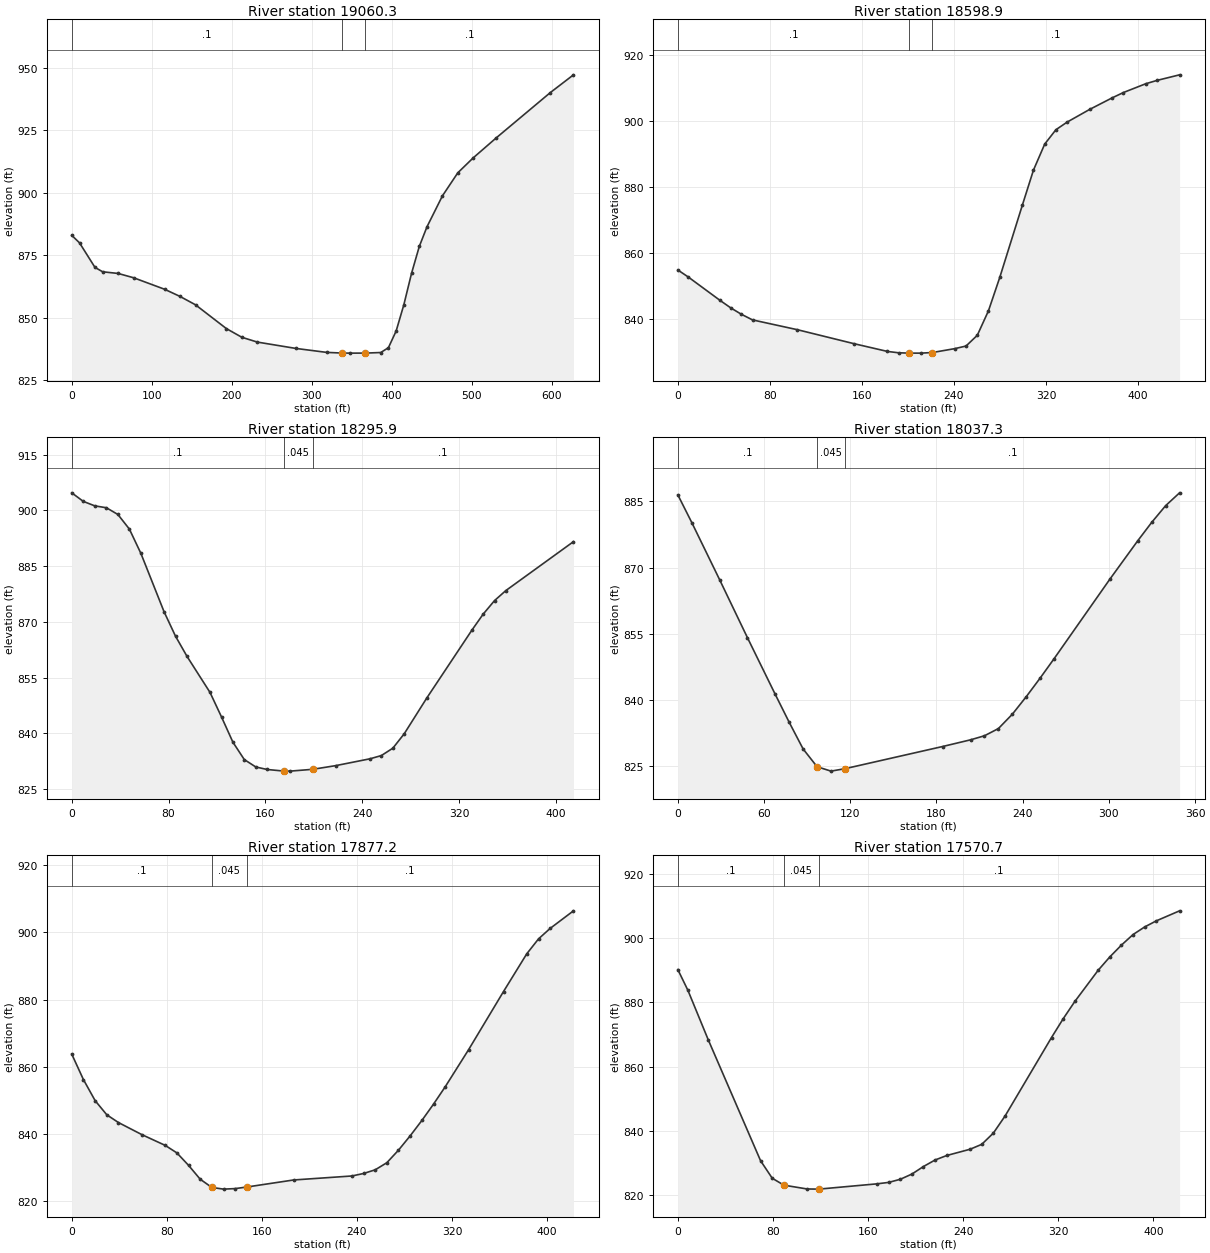
Type RM Length L Ch R = 1 ,19060.3 ,426.5,461.4,495.9
XS GIS Cut Line= 3
     1663668.817       747861.36     1663510.831       748017.61
     1663276.456      748347.471
#Sta/Elev= 30
       0  882.92     9.7  879.92      29   870.1    38.6  868.34      58  867.67
    77.3  865.95   115.9  861.36   135.2  858.49   154.6  855.13   193.2  845.61
   212.5  842.14   231.8  840.22     280  837.68   318.6  836.09   337.8  835.83
   347.4   835.8   366.7  835.81     386  836.04   395.6  837.97   405.3  844.68
   414.9  855.18   424.5  867.73   434.2   878.5   443.8  886.35   463.1  898.72
   482.3  907.94   501.6  913.93   530.5  921.96     598  940.06   626.8  947.13
#Mann= 3 , 0 , 0
       0      .1       0   337.8    .045       0   366.7      .1       0
Bank Sta=337.8,366.7
XS Rating Curve= 0 ,0
Exp/Cntr=0.3,0.1

Type RM Length L Ch R = 1 ,18598.9 ,324.8,303,281.3
XS GIS Cut Line= 3
     1663552.498      747854.415     1663526.456      747805.804
     1663205.276      747600.943
#Sta/Elev= 30
       0  855.01     9.2  852.84    36.8  845.76      46  843.52    55.2  841.59
    64.9  839.88     104   836.9   152.8   832.7   182.1  830.33   191.9  829.91
   200.9  829.82   201.7  829.81   211.4  829.81   221.2  829.99   240.7  831.17
   250.5  831.96   260.3  835.22     270  842.64   279.8  852.73   299.4  874.59
   309.1  885.26   318.9  893.16   328.6   897.5   338.4  899.82     358  903.67
   377.5  907.16   387.3  908.78   406.8  911.45   416.6  912.46   436.1  914.14
#Mann= 3 , 0 , 0
       0      .1       0   200.9    .045       0   221.2      .1       0
Bank Sta=200.9,221.2
XS Rating Curve= 0 ,0
Exp/Cntr=0.3,0.1

Type RM Length L Ch R = 1 ,18295.9 ,268.6,258.5,248.2
XS GIS Cut Line= 4
      1663641.04      747343.998     1663549.026      747411.707
     1663397.984      747465.526     1663271.248      747524.554
#Sta/Elev= 30
       0  904.75     9.5  902.45      19  901.24    28.6  900.73    38.1  898.92
    47.6  894.98    57.1  888.44    76.2  872.75    85.7  866.13    95.2  860.69
   114.2  850.98   123.7  844.37   133.1  837.58   142.5   832.9     152   830.9
   161.4  830.22     175   829.8   180.3  829.78   199.1  830.27     218  831.26
   246.3   833.1   255.7  833.97   265.2  835.96   274.6  839.84   293.2  849.46
   330.5  867.76   339.8  872.07   349.2  875.72   358.5  878.41   414.4   891.6
#Mann= 3 , 0 , 0
       0      .1       0     175    .045       0   199.1      .1       0
Bank Sta=175,199.1
XS Rating Curve= 0 ,0
Exp/Cntr=0.3,0.1

Type RM Length L Ch R = 1 ,18037.3 ,160.9,160.1,159.3
XS GIS Cut Line= 3
     1663448.331      747156.498     1663396.248      747199.901
     1663207.012      747408.235
#Sta/Elev= 23
       0   886.5     9.7  880.23    29.1  867.26    48.4  854.17    67.8  841.29
    77.5  834.97    87.2  828.92    96.9   824.9   106.6   823.9   116.3  824.45
   184.3  829.48   203.7  830.99   213.4  831.91   223.1  833.54   232.8  836.79
   242.5  840.77   252.2     845   261.9  849.39   300.7   867.4   320.1   876.1
   329.8  880.26   339.5  884.05   349.2  886.96
#Mann= 3 , 0 , 0
       0      .1       0    96.9    .045       0   116.3      .1       0
Bank Sta=96.9,116.3
XS Rating Curve= 0 ,0
Exp/Cntr=0.3,0.1

Type RM Length L Ch R = 1 ,17877.2 ,307.3,306.5,305.7
XS GIS Cut Line= 3
     1663358.054      747052.332     1663285.137      747081.846
     1663062.915      747343.998
#Sta/Elev= 30
       0  863.78     9.8  856.22    19.7  849.93    29.5  845.73    39.3  843.43
      59  839.84    78.7  836.63    88.5   834.4    98.3  830.71   108.1  826.58
   117.9  824.13   127.8  823.63   137.6  823.79   147.4  824.26   186.7  826.35
   235.8  827.54   245.6  828.28   255.4  829.37   265.2  831.48     275  835.21
   284.9   839.5   294.7  844.05   304.5   848.9   314.3  854.04     334  865.08
   363.4  882.38     383  893.61   392.9  898.05   402.7  901.16   422.3  906.38
#Mann= 3 , 0 , 0
       0      .1       0   117.9    .045       0   147.4      .1       0
Bank Sta=117.9,147.4
XS Rating Curve= 0 ,0
Exp/Cntr=0.3,0.1

Type RM Length L Ch R = 1 ,17570.7 ,167.6,169.6,171.5
XS GIS Cut Line= 3
     1663076.804      746828.373     1663050.762      746882.193
     1662826.804      747166.915
#Sta/Elev= 30
       0  890.26     8.5  883.76    25.6  868.32    69.6  830.58    79.4  825.12
    89.2  822.96   108.7  821.77   118.5  821.72   118.6  821.72   167.5  823.37
   177.3  823.82   187.1  824.79   196.9  826.43   206.6  828.78   216.4  830.82
   226.2  832.22   245.8  834.17   255.6   835.7   265.4  839.22   275.2  844.53
   314.3  869.05   324.1   874.9   333.9   880.3   353.5  890.03   363.3   894.2
   373.1   897.9   382.9   901.2   392.7  903.58   402.5  905.48     422   908.6
#Mann= 3 , 0 , 0
       0      .1       0    89.2    .045       0   118.6      .1       0
Bank Sta=89.2,118.6
XS Rating Curve= 0 ,0
Exp/Cntr=0.3,0.1