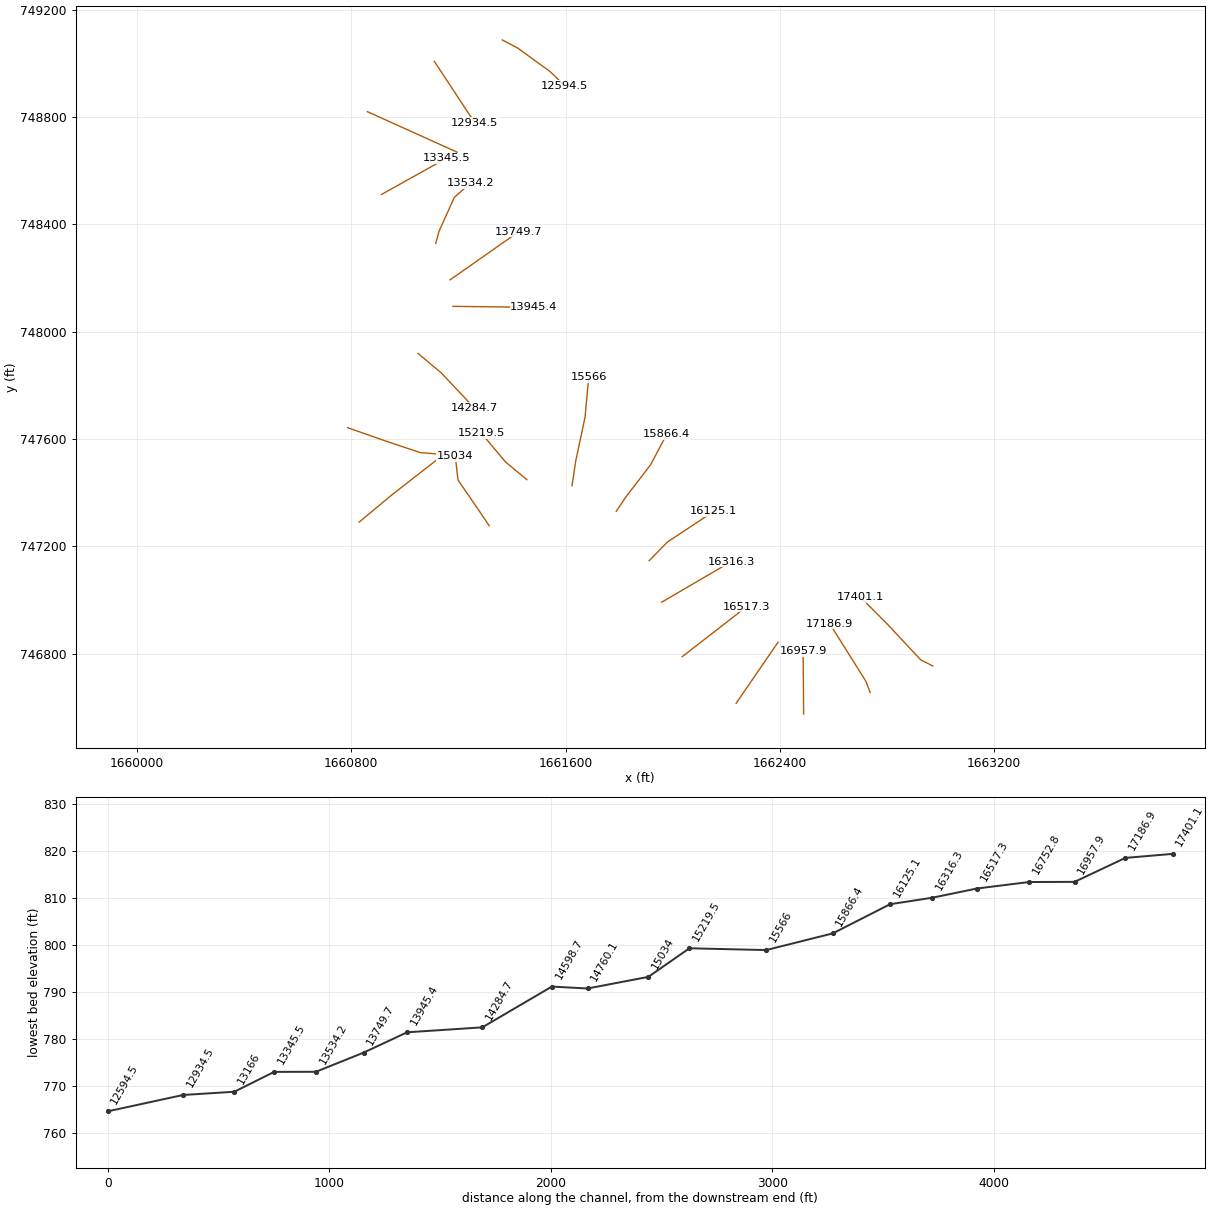
HEC-RAS study TOMLINRN.prj: TOMLINRN

--- TOMLINRN.g01 (geometry) --- (continued)

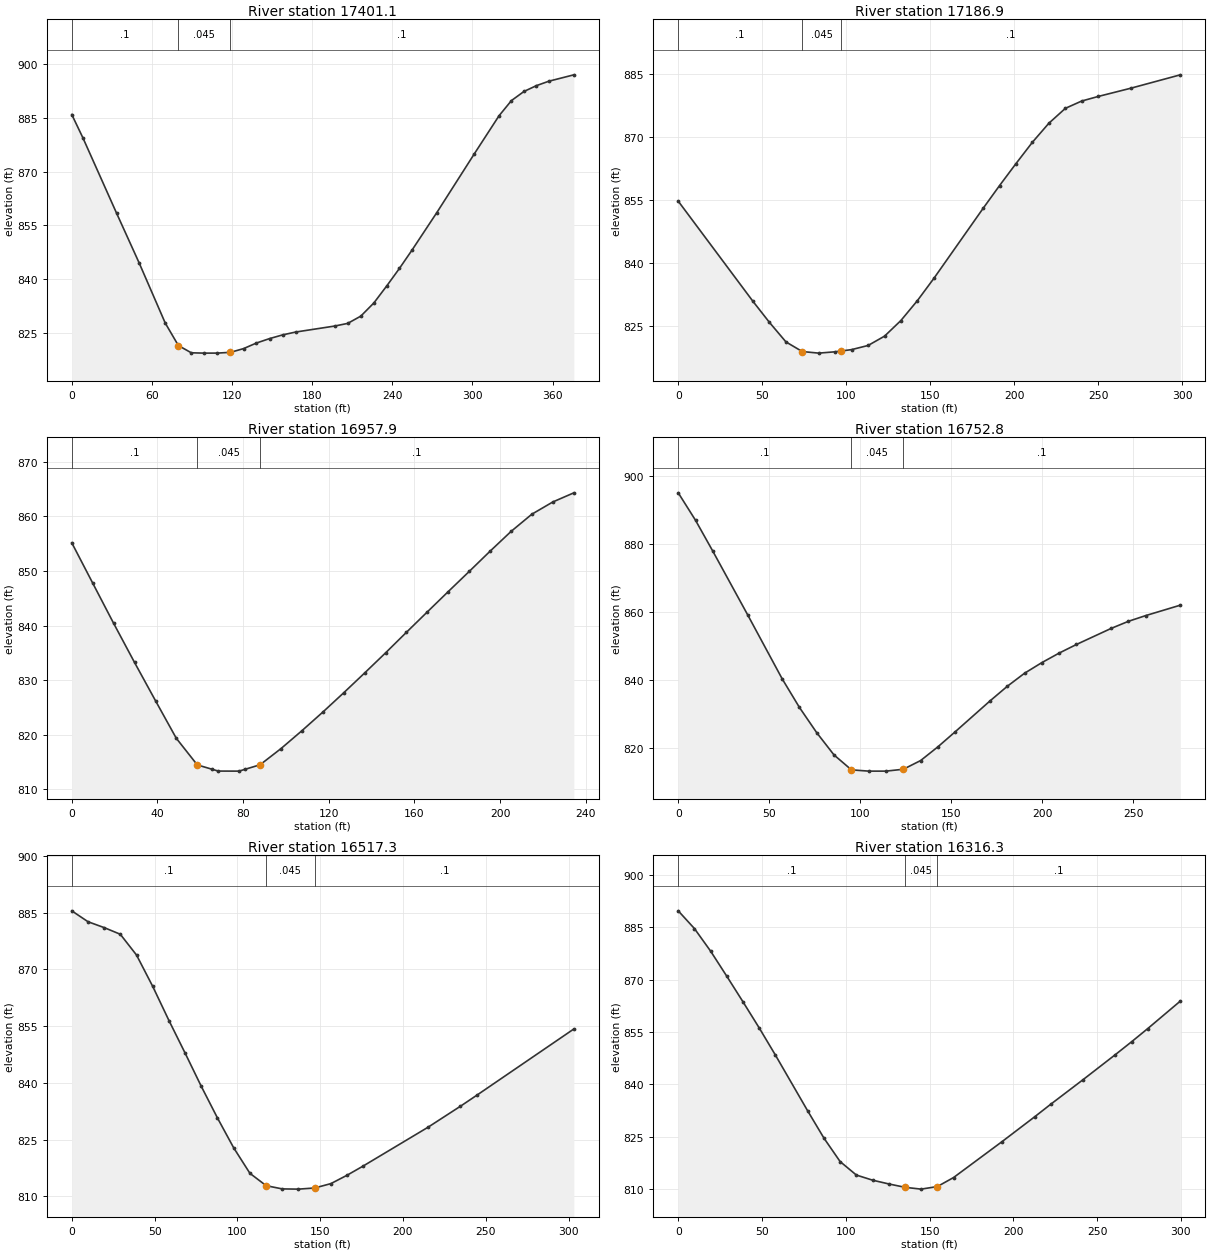
Type RM Length L Ch R = 1 ,17401.1 ,218.8,214.2,209.6
XS GIS Cut Line= 4
     1662970.901      746753.721     1662925.762       746776.29
     1662799.026      746911.707     1662700.067      747010.665
#Sta/Elev= 30
       0  885.97     8.4   879.4    33.6  858.36    50.5  844.46      70  827.69
    79.8  821.43    89.5  819.39    99.3   819.3     109  819.31   118.8  819.52
   128.6  820.56   138.3  822.13   148.1  823.36   157.8  824.39   167.6  825.19
   196.9  826.87   206.6  827.61   216.4  829.64   226.2  833.33   235.9  838.12
   245.3  842.96   254.6  848.01   273.3  858.56   301.2  874.88   319.9  885.63
   329.2  889.87   338.6  892.42   347.9  894.04   357.2  895.28   375.9  897.06
#Mann= 3 , 0 , 0
       0      .1       0    79.8    .045       0   118.8      .1       0
Bank Sta=79.8,118.8
XS Rating Curve= 0 ,0
Exp/Cntr=0.3,0.1

Type RM Length L Ch R = 1 ,17186.9 ,241.5,229,216.5
XS GIS Cut Line= 3
     1662736.526      746654.762     1662720.901      746696.429
     1662585.484      746911.707
#Sta/Elev= 24
       0  854.73    44.5  830.79    54.3  825.77    64.1  821.12    73.8  818.82
    83.6  818.44    93.4  818.76    96.8  818.94   103.2  819.28     113  820.27
   122.8   822.5   132.5  826.22   142.3  830.96   152.1  836.27   181.4  852.99
   191.2  858.44     201   863.7   210.8  868.81   220.6  873.35   230.4   876.9
   240.1  878.64   249.9  879.73   269.5  881.72   298.8   884.9
#Mann= 3 , 0 , 0
       0      .1       0    73.8    .045       0    96.8      .1       0
Bank Sta=73.8,96.8
XS Rating Curve= 0 ,0
Exp/Cntr=0.3,0.1

Type RM Length L Ch R = 1 ,16957.9 ,218.7,205,191.2
XS GIS Cut Line= 2
     1662488.262      746574.901     1662486.526      746809.276
#Sta/Elev= 27
       0  855.14     9.8  847.74    19.5  840.43    29.3  833.24    39.1  826.23
    48.8  819.36    58.6  814.49    65.7  813.67    68.4  813.36    78.1  813.35
    80.7  813.66    87.9  814.51    97.7  817.48   107.4  820.73   117.2  824.15
     127   827.7   136.7   831.3   146.5  834.99   156.2  838.74     166  842.49
   175.8  846.22   185.6  849.91   195.3   853.6   205.1  857.22   214.8  860.37
   224.6  862.61   234.4  864.28
#Mann= 3 , 0 , 0
       0      .1       0    58.6    .045       0    87.9      .1       0
Bank Sta=58.6,87.9
XS Rating Curve= 0 ,0
Exp/Cntr=0.3,0.1

Type RM Length L Ch R = 1 ,16752.8 ,242.4,235.5,228.9
XS GIS Cut Line= 2
     1662236.526      746614.832     1662392.776      746842.262
#Sta/Elev= 25
       0  895.14     9.5  887.07      19  877.99    38.1  859.32    57.1  840.47
    66.6  832.05    76.1  824.62    85.6  818.08    95.2  813.69   104.7  813.32
   114.1  813.32   123.7  813.87   133.2  816.43   142.7  820.47   152.2  824.89
   171.3  833.95   180.8  838.25   190.3   842.1   199.8  845.22   209.3  848.02
   218.8  850.55   237.9  855.28   247.4  857.37   256.9  859.05   275.9  862.11
#Mann= 3 , 0 , 0
       0      .1       0    95.2    .045       0   123.7      .1       0
Bank Sta=95.2,123.7
XS Rating Curve= 0 ,0
Exp/Cntr=0.3,0.1

Type RM Length L Ch R = 1 ,16517.3 ,203.9,201,197.3
XS GIS Cut Line= 2
     1662035.137      746788.443      1662274.72      746974.207
#Sta/Elev= 23
       0  885.48     9.8   882.6    19.6  881.04    29.3  879.29    39.1   873.8
    48.9   865.5    58.7  856.48    68.5  847.84    78.2  839.11      88  830.73
    97.8  822.84   107.6  816.11   117.4  812.85   127.1     812   136.9  811.94
   146.7  812.24   156.5   813.4   166.2   815.6     176  818.05   215.2  828.31
   234.7  833.84   244.5  836.72   303.2  854.26
#Mann= 3 , 0 , 0
       0      .1       0   117.4    .045       0   146.7      .1       0
Bank Sta=117.4,146.7
XS Rating Curve= 0 ,0
Exp/Cntr=0.3,0.1

Type RM Length L Ch R = 1 ,16316.3 ,190.1,191.2,192.5
XS GIS Cut Line= 2
     1661958.748      746991.568     1662217.429       747142.61
#Sta/Elev= 25
       0  889.69     9.7  884.59    19.3  878.16      29  870.94    38.6  863.66
    48.3  856.17      58  848.37    77.3  832.35      87  824.56    96.6  817.88
   106.3  814.02     116  812.55   125.6  811.48   135.3  810.51   144.9  809.99
   154.6  810.72   164.3  813.31   193.3  823.62   212.6  830.67   222.2  834.27
   241.6  841.35   260.9  848.53   270.6  852.22   280.2  855.98   299.6  863.84
#Mann= 3 , 0 , 0
       0      .1       0   135.3    .045       0   154.6      .1       0
Bank Sta=135.3,154.6
XS Rating Curve= 0 ,0
Exp/Cntr=0.3,0.1

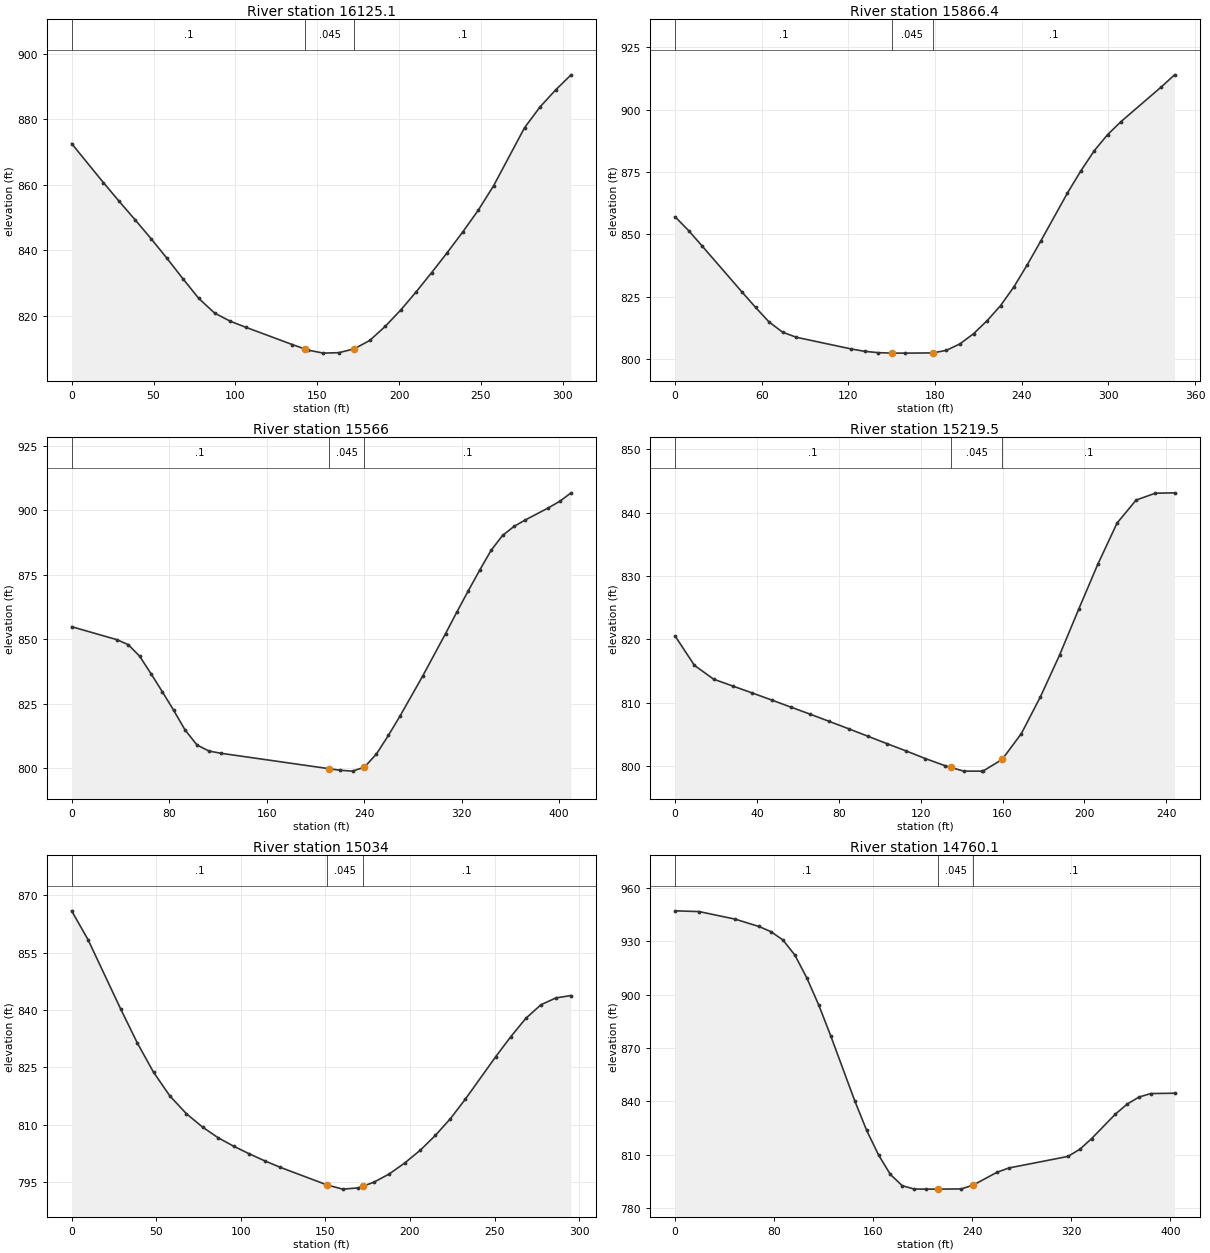
Type RM Length L Ch R = 1 ,16125.1 ,250.9,258.7,266.5
XS GIS Cut Line= 3
     1661911.873      747146.082     1661979.581      747215.526
     1662153.192       747330.11
#Sta/Elev= 30
       0  872.62    19.4   860.7    29.1  854.93    38.8  849.32    48.5  843.57
    58.2  837.59    67.9  831.37    77.6  825.34    87.3  820.84      97  818.32
   106.4   816.5   134.8  811.21   142.7  809.82   144.3  809.54   153.7   808.6
   163.2  808.74   172.6  809.91   182.1  812.49   191.5  816.77     201  821.78
   210.4  827.31   219.9  833.23   229.4  839.31   238.8  845.58   248.3  852.24
   257.7  859.74   276.6  877.47   286.1  883.84   295.6  889.02     305  893.62
#Mann= 3 , 0 , 0
       0      .1       0   142.7    .045       0   172.6      .1       0
Bank Sta=142.7,172.6
XS Rating Curve= 0 ,0
Exp/Cntr=0.3,0.1

Type RM Length L Ch R = 1 ,15866.4 ,290.3,300.4,310.5
XS GIS Cut Line= 4
     1661788.609       747330.11     1661825.067      747383.929
     1661917.081      747503.721     1661977.845      747618.304
#Sta/Elev= 29
       0  857.05     9.3  851.54    18.6   845.4    46.4  826.83    55.7  820.72
      65   814.9    74.4  810.79    83.9  808.76   121.6  804.11   131.1  803.13
   140.5  802.59     150  802.41   159.4   802.4   178.3  802.49   187.7   803.5
   197.2  806.12   206.6  810.19   216.1  815.48   225.3  821.45   234.6  829.03
   243.8  837.84   253.1   847.3   271.6  866.59   280.9  875.49   290.2  883.59
   299.4     890   308.7  895.24   336.5   909.1   345.8  913.99
#Mann= 3 , 0 , 0
       0      .1       0     150    .045       0   178.3      .1       0
Bank Sta=150,178.3
XS Rating Curve= 0 ,0
Exp/Cntr=0.3,0.1

Type RM Length L Ch R = 1 ,15566   ,325.7,346.4,366.8
XS GIS Cut Line= 4
     1661623.679      747425.596     1661637.567       747517.61
      1661672.29      747680.804     1661686.179       747830.11
#Sta/Elev= 30
       0  854.88    37.2  849.84    46.5   847.9    55.8  843.43    65.1  836.68
    74.4  829.67    83.8  822.39    93.1  814.81   102.9  808.99   112.7  806.65
   122.5  805.79   210.8  799.83   220.6  799.18   230.5  798.86   240.3  800.43
   250.1   805.5   259.9  812.71   269.3   820.1     288  835.69   306.8  852.18
   316.1  860.57   325.5  868.83   334.9  876.87   344.2  884.51   353.6  890.27
     363  893.78   372.4  896.31   391.1  900.95   400.5   903.5   409.8   906.8
#Mann= 3 , 0 , 0
       0      .1       0   210.8    .045       0   240.3      .1       0
Bank Sta=210.8,240.3
XS Rating Curve= 0 ,0
Exp/Cntr=0.3,0.1

Type RM Length L Ch R = 1 ,15219.5 ,187.7,185.6,183.5
XS GIS Cut Line= 3
     1661455.276      747448.165     1661375.415      747514.137
     1661285.137      747621.776
#Sta/Elev= 29
       0  820.53     9.4  815.92    18.8  813.74    28.2  812.65    37.7  811.56
    47.1  810.46    56.5  809.34    65.9  808.23    75.3  807.08    84.8  805.92
    94.2  804.74   103.6  803.56     113  802.41   122.3  801.22   131.7  800.12
   134.9  799.82     141  799.24   149.9  799.24   150.4  799.24   159.8  801.08
   169.2  805.16   178.5  810.95   187.9  817.55   197.2  824.75   206.6  831.88
     216  838.36   225.3  841.98   234.7  843.06   244.1  843.12
#Mann= 3 , 0 , 0
       0      .1       0   134.9    .045       0   159.8      .1       0
Bank Sta=134.9,159.8
XS Rating Curve= 0 ,0
Exp/Cntr=0.3,0.1

Type RM Length L Ch R = 1 ,15034   ,308.2,273.9,239.5
XS GIS Cut Line= 4
     1661314.651       747276.29     1661271.248      747340.526
     1661198.331      747446.429     1661187.915      747534.971
#Sta/Elev= 30
       0  865.94     9.7  858.39    29.1  840.17    38.8  831.41    48.4  823.74
    58.1  817.51    67.8   812.9    77.5  809.35    86.7  806.57    95.9  804.36
   105.1  802.37   114.3  800.53   123.4  798.85     151  794.25   160.2  793.16
   169.4  793.48   172.4  793.96   178.6  794.96   187.7  797.12   196.9     800
   206.1  803.35     215  807.21   223.9   811.6   232.8  816.74   250.7  827.82
   259.6  833.04   268.5  837.84   277.4  841.38   286.3  843.17   295.2  843.79
#Mann= 3 , 0 , 0
       0      .1       0     151    .045       0   172.4      .1       0
Bank Sta=151,172.4
XS Rating Curve= 0 ,0
Exp/Cntr=0.3,0.1

Type RM Length L Ch R = 1 ,14760.1 ,183.5,161.4,138.9
XS GIS Cut Line= 3
     1660829.408      747290.179     1660948.331      747389.137
     1661144.512      747541.915
#Sta/Elev= 30
       0  947.15    19.3  946.73    48.4  942.49    67.7  938.34    77.4  935.42
      87  930.79    96.7  922.27   106.4  909.34     116  894.14   125.7  876.78
     145  840.45   154.7  823.69   164.3  809.89   173.8     799   183.4  792.63
     193  790.76   202.5   790.7   212.1   790.7   231.2  790.82   240.8     793
   259.9  800.16   269.5  802.59   317.3  809.09   326.9  813.14   336.4  819.13
   355.6  832.88   365.1  838.51   374.7  842.47   384.2  844.43   403.4  844.61
#Mann= 3 , 0 , 0
       0      .1       0   212.1    .045       0   240.8      .1       0
Bank Sta=212.1,240.8
XS Rating Curve= 0 ,0
Exp/Cntr=0.3,0.1

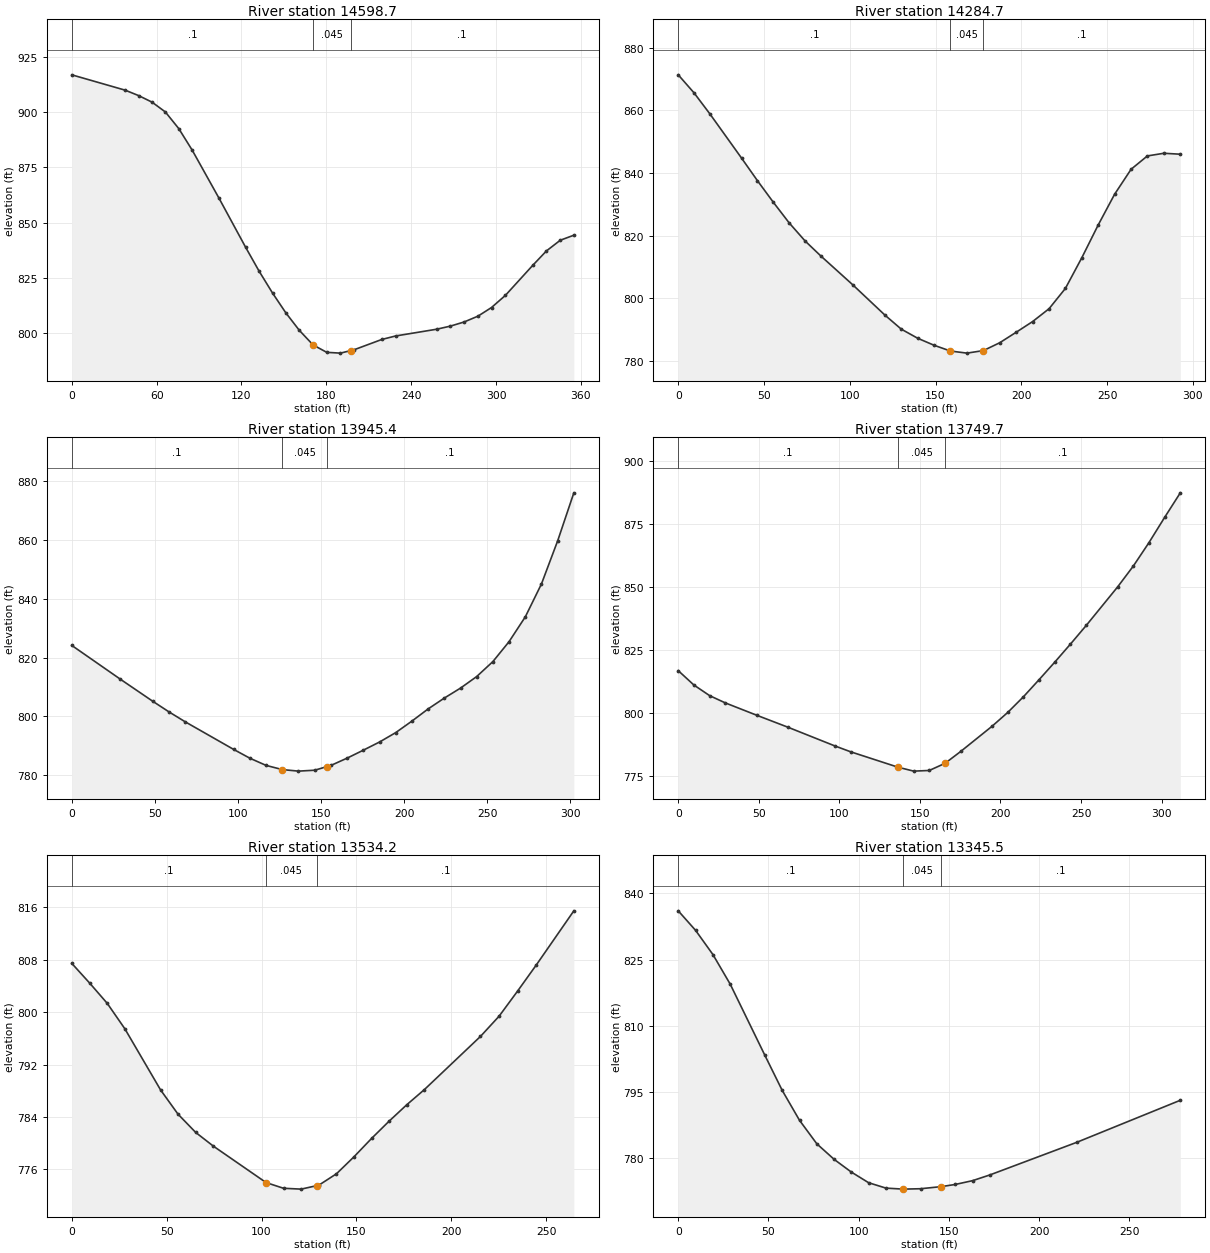
Type RM Length L Ch R = 1 ,14598.7 ,324.9,314,302.5
XS GIS Cut Line= 4
     1660786.005      747641.741     1660937.915       747588.79
     1661057.706       747548.86     1661125.415      747543.651
#Sta/Elev= 30
       0  916.83    37.8  909.89    47.3  907.44    56.8  904.47    66.2  900.04
    75.7   892.5    85.2  882.75   104.1   861.1     123  838.84   132.5  828.08
     142   818.2   151.4  809.26   160.9  801.39   170.6  794.81   180.3  791.45
     190   791.1   197.1  792.23   199.7  792.64   219.2  797.27   228.9  798.84
     258   801.9   267.7   803.3   277.4  805.17   287.2   807.8   296.8  811.71
   306.6  817.19     326   830.8   335.6  837.26   345.4   842.1     355  844.37
#Mann= 3 , 0 , 0
       0      .1       0   170.6    .045       0   197.1      .1       0
Bank Sta=170.6,197.1
XS Rating Curve= 0 ,0
Exp/Cntr=0.3,0.1

Type RM Length L Ch R = 1 ,14284.7 ,321.1,339.3,357.5
XS GIS Cut Line= 3
     1661049.026      747918.651     1661134.095      747847.471
     1661259.095      747715.526
#Sta/Elev= 29
       0  871.31     9.2  865.56    18.5   858.8      37  844.65    46.2  837.49
    55.5  830.57    64.7  824.01      74  818.23    83.2  813.43   101.7  804.28
   120.5  794.58     130  790.11   139.6  787.19   149.2  784.94   158.7  783.11
   168.3  782.44   177.9  783.25   187.4  785.75     197   789.1   206.6  792.52
   216.2  796.63   225.7   803.1   235.3  812.92   244.8  823.33   254.4  833.18
     264  841.15   273.5  845.41   283.1  846.26   292.7  845.96
#Mann= 3 , 0 , 0
       0      .1       0   158.7    .045       0   177.9      .1       0
Bank Sta=158.7,177.9
XS Rating Curve= 0 ,0
Exp/Cntr=0.3,0.1

Type RM Length L Ch R = 1 ,13945.4 ,181.6,195.7,209.8
XS GIS Cut Line= 2
     1661179.234      748093.998     1661481.317      748090.526
#Sta/Elev= 28
       0  824.11    29.2  812.64    48.7  805.14    58.5  801.52    68.2  798.17
    97.4  788.77   107.2  785.77   116.9  783.34   126.7  781.91   136.4  781.39
   146.2   781.7   153.3  782.89   155.9  783.32   165.7  785.81   175.4   788.5
   185.2  791.29   194.9  794.47   204.6  798.36   214.4  802.52   224.1  806.19
   233.9   809.6   243.6  813.51   253.4  818.62   263.1  825.37   272.9  833.82
   282.6  844.98   292.4   859.7   302.1  875.96
#Mann= 3 , 0 , 0
       0      .1       0   126.7    .045       0   153.3      .1       0
Bank Sta=126.7,153.3
XS Rating Curve= 0 ,0
Exp/Cntr=0.3,0.1

Type RM Length L Ch R = 1 ,13749.7 ,203.2,215.6,227.7
XS GIS Cut Line= 2
     1661168.817      748192.957     1661424.026      748371.776
#Sta/Elev= 25
       0  816.94     9.7  811.25    19.5  807.02    29.2  804.15    48.7  799.25
    68.2  794.47    97.4  787.03   107.1  784.73   136.3  778.66   146.1  777.08
   155.8  777.34   165.6  780.18   175.3  784.88   194.8   794.9   204.5  800.36
   214.2  806.55     224   813.4   233.7  820.32   243.4  827.46   253.2  834.86
   272.7  850.16   282.4   858.4   292.1  867.68   301.9  877.77   311.6  887.48
#Mann= 3 , 0 , 0
       0      .1       0   136.3    .045       0   165.6      .1       0
Bank Sta=136.3,165.6
XS Rating Curve= 0 ,0
Exp/Cntr=0.3,0.1

Type RM Length L Ch R = 1 ,13534.2 ,203.2,188.6,174.1
XS GIS Cut Line= 4
     1661114.998      748328.373     1661127.151      748373.512
     1661184.442      748500.248      1661243.47      748552.332
#Sta/Elev= 24
       0  807.43     9.4  804.43    18.7  801.33      28  797.44    46.8  788.13
      56  784.43    65.3  781.65    74.6  779.56   102.4     774   111.6  773.13
   120.9     773   129.1  773.53   130.2   773.6   139.5  775.34   148.7  777.92
     158  780.73   167.3  783.38   176.6  785.88   185.8  788.17   215.4  796.29
   225.2  799.37     235  803.22   244.9  807.22   264.6  815.44
#Mann= 3 , 0 , 0
       0      .1       0   102.4    .045       0   129.1      .1       0
Bank Sta=102.4,129.1
XS Rating Curve= 0 ,0
Exp/Cntr=0.3,0.1

Type RM Length L Ch R = 1 ,13345.5 ,200.8,179.6,158.4
XS GIS Cut Line= 2
     1660911.873      748510.665     1661154.929      748646.082
#Sta/Elev= 20
       0  836.06     9.6  831.64    19.2  826.16    28.8  819.44      48  803.32
    57.6  795.37    67.2  788.58    76.8  783.25    86.4  779.72    95.9  776.85
   105.5  774.43   115.1  773.21   124.7  772.98   134.3  773.07   145.8  773.55
   153.5  774.04   163.1   774.9   172.7   776.2   220.7  783.57   278.2  793.12
#Mann= 3 , 0 , 0
       0      .1       0   124.7    .045       0   145.8      .1       0
Bank Sta=124.7,145.8
XS Rating Curve= 0 ,0
Exp/Cntr=0.3,0.1

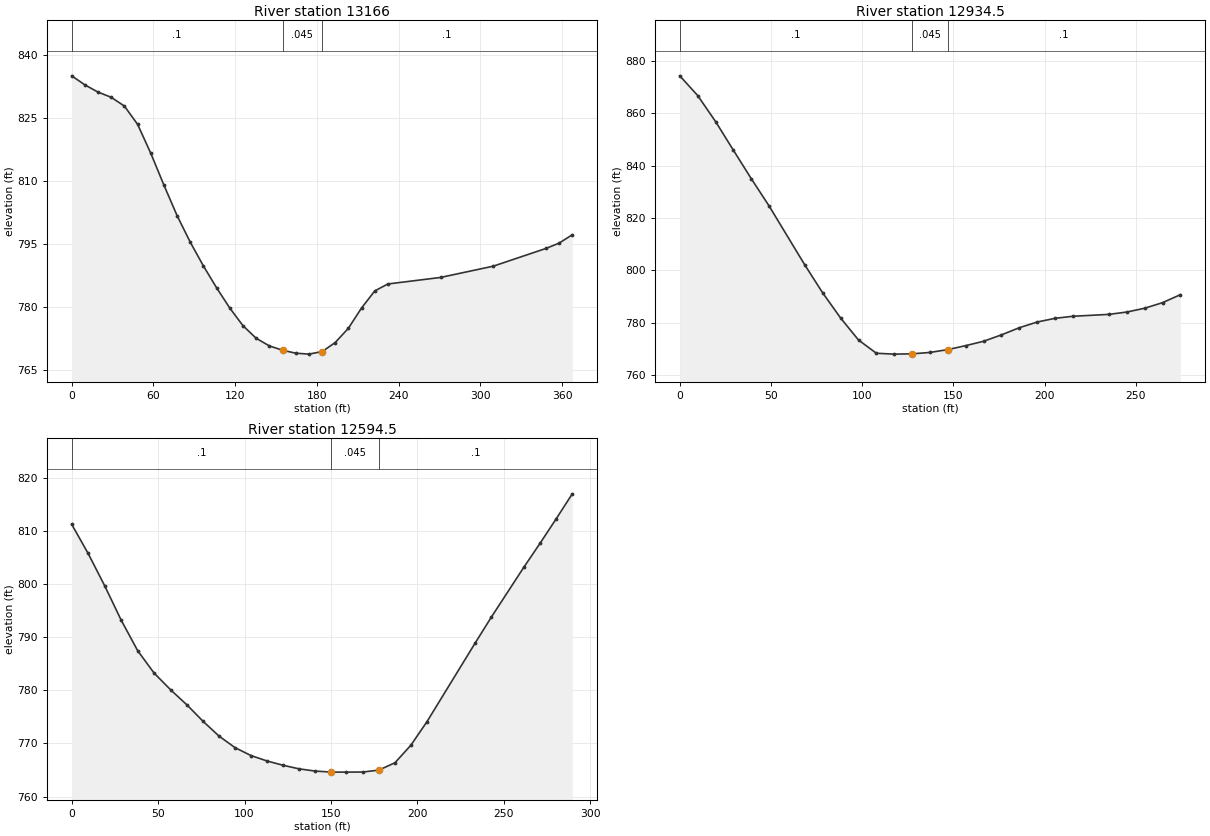
Type RM Length L Ch R = 1 ,13166   ,244.2,231.5,218.6
XS GIS Cut Line= 2
      1660859.79      748819.693     1661194.859      748668.651
#Sta/Elev= 30
       0  835.14     9.7  832.98    19.3  831.26      29  830.02    38.7  827.92
    48.4  823.56      58  816.71    67.7  809.08    77.4  801.78      87  795.49
    96.7  789.79   106.4  784.57   116.1  779.73   125.7  775.56   135.4  772.55
   145.1  770.72   154.8  769.69   164.4  768.99   174.1  768.76   183.8  769.36
   193.4  771.51   203.1  774.92   212.8  779.77   222.5  783.84   232.1  785.49
   270.8  787.05   309.5  789.74   348.2  793.97   357.9  795.25   367.5  797.23
#Mann= 3 , 0 , 0
       0      .1       0   154.8    .045       0   183.8      .1       0
Bank Sta=154.8,183.8
XS Rating Curve= 0 ,0
Exp/Cntr=0.3,0.1

Type RM Length L Ch R = 1 ,12934.5 ,331.6,340,348.2
XS GIS Cut Line= 2
      1661109.79      749007.193     1661260.831      748778.026
#Sta/Elev= 27
       0  874.21     9.8   866.7    19.6  856.79    29.4  845.83    39.2  834.98
      49  824.54    68.6  802.03    78.4  791.38    88.2  781.83      98  773.45
   107.8   768.4   117.6  768.07   127.4  768.18   137.2  768.72     147   769.8
   156.8  771.31   166.6  772.98   176.4  775.42   186.2  778.15     196  780.32
   205.8  781.73   215.6  782.51   235.3  783.23   245.1  784.12   254.9  785.57
   264.7   787.7   274.5  790.74
#Mann= 3 , 0 , 0
       0      .1       0   127.4    .045       0     147      .1       0
Bank Sta=127.4,147
XS Rating Curve= 0 ,0
Exp/Cntr=0.3,0.1

Type RM Length L Ch R = 1 ,12594.5 ,161.4,187.4,213.2
XS GIS Cut Line= 4
     1661363.262      749087.054      1661422.29      749055.804
     1661542.081      748968.998     1661595.901      748916.915
#Sta/Elev= 29
       0  811.26     9.5  805.78    19.1  799.68    28.6  793.23    38.2  787.45
    47.7  783.24    57.2  780.11    66.8  777.22      76  774.17    85.3  771.37
    94.5  769.21   103.8  767.71     113   766.7   122.3  765.89   131.5  765.22
   140.8   764.8     150  764.61   158.6   764.6   168.5  764.62   177.7  764.98
     187  766.36   196.2  769.66   205.5  774.08   233.4   788.9   242.8   793.8
   261.5  803.14   270.9  807.66   280.3   812.3   289.6     817
#Mann= 3 , 0 , 0
       0      .1       0     150    .045       0   177.7      .1       0
Bank Sta=150,177.7
XS Rating Curve= 0 ,0
Exp/Cntr=0.3,0.1