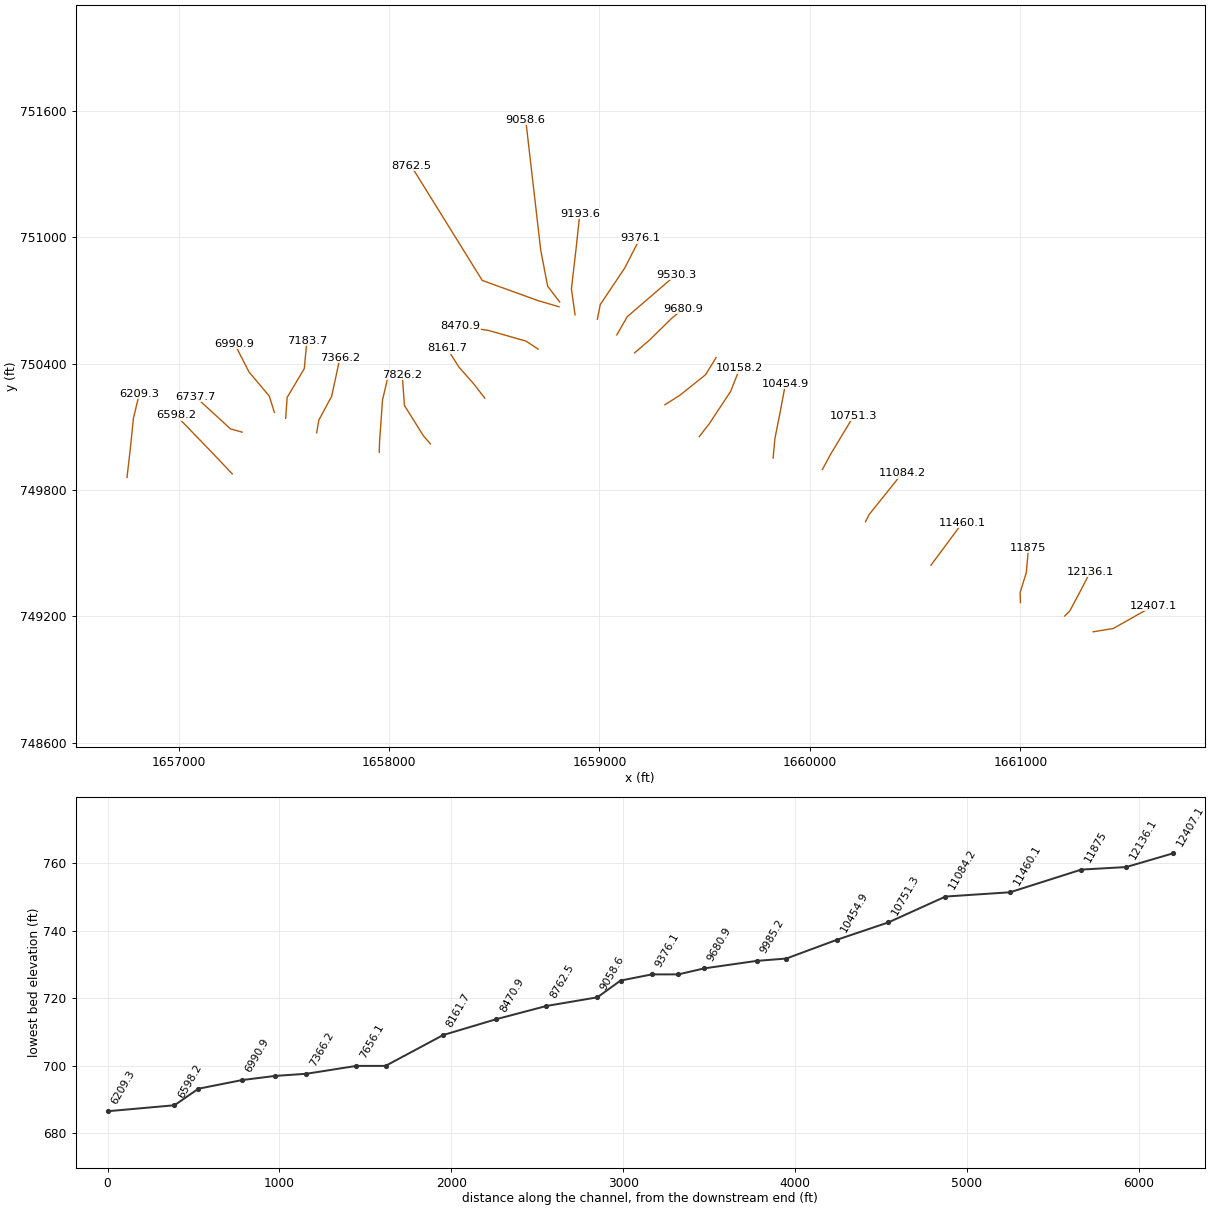
HEC-RAS study TOMLINRN.prj: TOMLINRN

--- TOMLINRN.g01 (geometry) --- (continued)

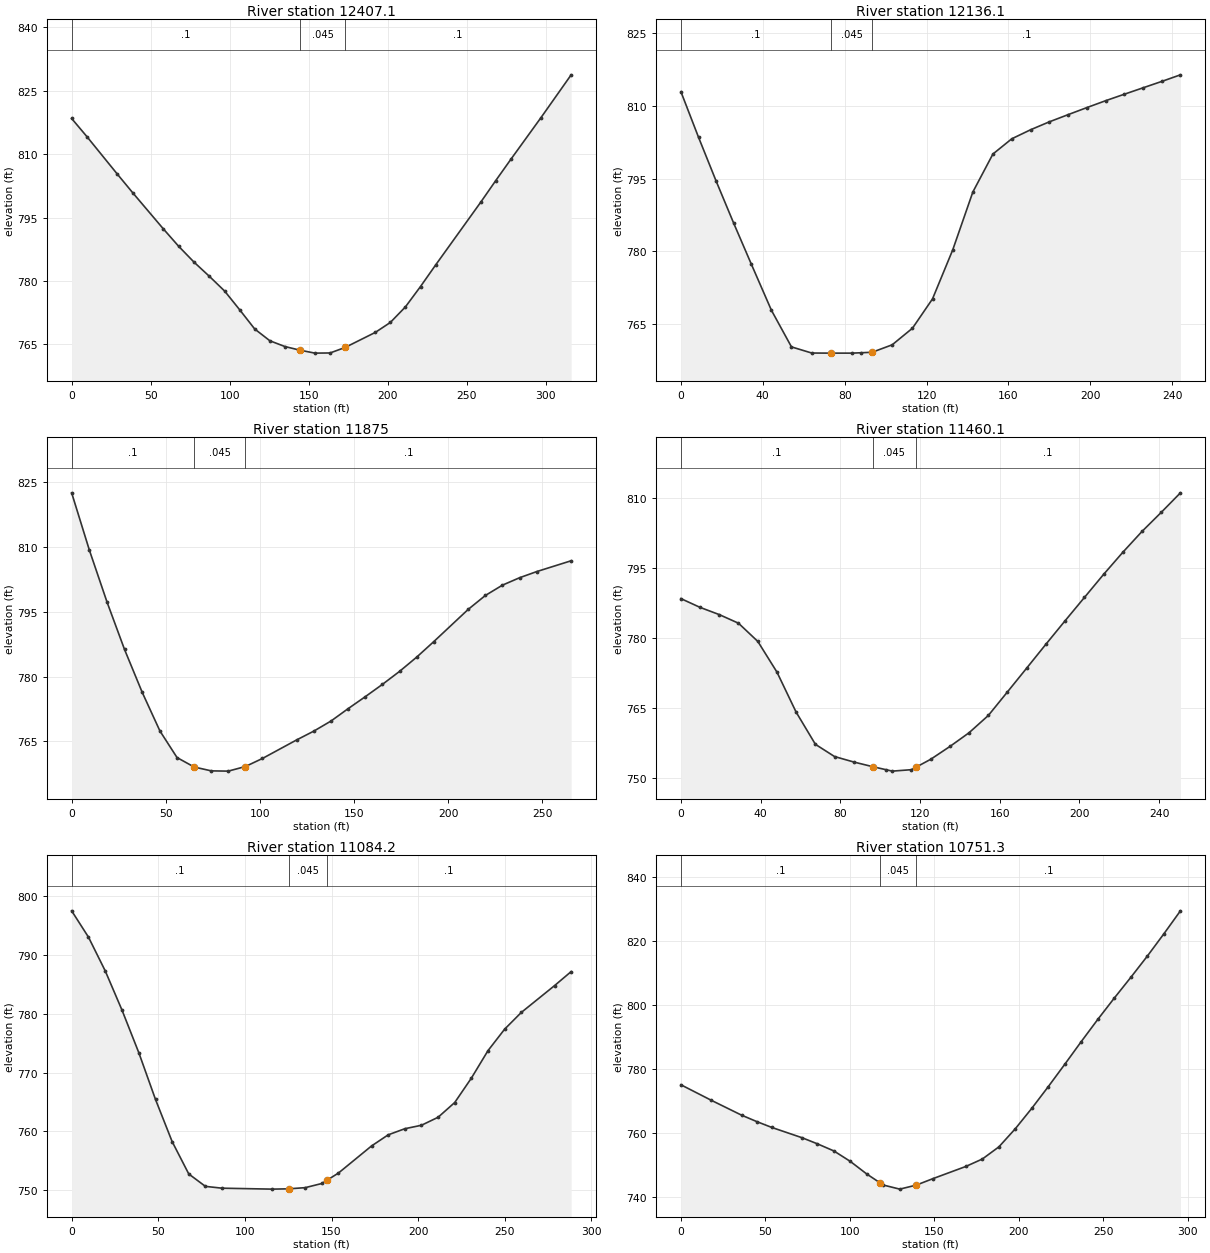
Type RM Length L Ch R = 1 ,12407.1 ,258,270.9,283.8
XS GIS Cut Line= 3
     1661345.901      749126.985     1661441.387       749142.61
     1661632.359      749250.248
#Sta/Elev= 27
       0  818.42     9.7  814.11      29  805.22    38.7  800.83      58  792.32
    67.7   788.2    77.4  784.46    87.1  781.11    96.8  777.61   106.3  773.19
   115.8  768.65   125.4  765.86   134.9   764.5   144.4  763.64   153.9  762.94
   163.5  762.98     173  764.28   192.1  767.84   201.6  770.19   211.1  773.85
   220.7  778.69   230.2  783.75   258.8  798.63   268.3  803.74   277.8  808.74
   296.9  818.62     316  828.74
#Mann= 3 , 0 , 0
       0      .1       0   144.4    .045       0     173      .1       0
Bank Sta=144.4,173
XS Rating Curve= 0 ,0
Exp/Cntr=0.3,0.1

Type RM Length L Ch R = 1 ,12136.1 ,256.7,261.1,265.4
XS GIS Cut Line= 4
     1661210.484      749201.637      1661234.79      749225.943
     1661290.345       749330.11     1661332.012      749411.707
#Sta/Elev= 29
       0  812.96     8.6  803.54    17.2  794.48    25.8  785.75    34.4  777.29
    44.2  767.77      54  760.19    63.9  758.92    73.2   758.9    73.7   758.9
    83.6   758.9    88.2  758.98    93.4  759.08   103.2  760.62   113.1  764.05
   122.9  770.12   132.8  780.28   142.6  792.22   152.4  800.07   161.6  803.22
   170.8  805.09   179.9  806.72   189.1  808.21   198.2  809.66   207.4  811.09
   216.6  812.44   225.7  813.76   234.9  815.09     244  816.45
#Mann= 3 , 0 , 0
       0      .1       0    73.2    .045       0    93.4      .1       0
Bank Sta=73.2,93.4
XS Rating Curve= 0 ,0
Exp/Cntr=0.3,0.1

Type RM Length L Ch R = 1 ,11875   ,422.6,414.9,407.3
XS GIS Cut Line= 4
     1661000.415      749265.873     1660998.679      749312.748
     1661028.192      749408.235     1661038.609       749526.29
#Sta/Elev= 27
       0  822.43     9.4  809.22    18.8   797.2    28.1  786.25    37.5  776.34
    46.9  767.43      56  761.28    65.1   759.1    74.2  758.21    83.2  758.15
    92.3  759.21   101.4  761.08   119.6  765.37   128.7   767.4   137.8  769.72
   146.8  772.55     156  775.34   165.1  778.18   174.2  781.18   183.3  784.47
   192.4  788.06   210.7  795.51   219.8  798.72   228.9  801.11     238  802.82
   247.1  804.24   265.4  806.74
#Mann= 3 , 0 , 0
       0      .1       0    65.1    .045       0    92.3      .1       0
Bank Sta=65.1,92.3
XS Rating Curve= 0 ,0
Exp/Cntr=0.3,0.1

Type RM Length L Ch R = 1 ,11460.1 ,376.7,375.8,375
XS GIS Cut Line= 2
     1660575.067      749442.957     1660724.373      749644.346
#Sta/Elev= 29
       0  788.45     9.6  786.57    19.3  785.01    28.9  783.17    38.6  779.26
    48.2  772.68    57.8  764.11    67.5  757.18    77.1  754.56    86.8  753.38
    96.4  752.37   102.9  751.74   106.1  751.43   115.7  751.74   117.9  752.25
   125.4  753.98     135  756.72   144.6  759.66   154.3  763.38   163.9  768.44
   173.6  773.57   183.2  778.67   192.8  783.69   202.5  788.69   212.1  793.63
   221.8   798.4   231.4  802.86   241.1  806.97   250.7  811.15
#Mann= 3 , 0 , 0
       0      .1       0    96.4    .045       0   117.9      .1       0
Bank Sta=96.4,117.9
XS Rating Curve= 0 ,0
Exp/Cntr=0.3,0.1

Type RM Length L Ch R = 1 ,11084.2 ,329.8,332.9,335.9
XS GIS Cut Line= 3
     1660264.304      749649.554     1660281.665      749684.276
     1660437.915      749878.721
#Sta/Elev= 28
       0  797.52     9.7  793.05    19.4  787.29    29.1   780.6    38.8  773.35
    48.4  765.42      58  758.25    67.6  752.74    77.2  750.63    86.8  750.32
   115.6  750.16   125.2  750.21   134.8  750.41   144.4  751.12   147.4  751.68
     154   752.9   173.1  757.51   182.7   759.4   192.3  760.44   201.9  761.03
   211.5  762.39   221.1   764.9   230.7  769.05   240.3  773.73   249.9  777.38
   259.5  780.22   278.7  784.79   288.3  787.18
#Mann= 3 , 0 , 0
       0      .1       0   125.2    .045       0   147.4      .1       0
Bank Sta=125.2,147.4
XS Rating Curve= 0 ,0
Exp/Cntr=0.3,0.1

Type RM Length L Ch R = 1 ,10751.3 ,288.4,296.5,304.2
XS GIS Cut Line= 3
     1660059.442      749897.818     1660097.637      749968.998
     1660208.748      750153.026
#Sta/Elev= 29
       0   775.1      18  770.25    35.9  765.61    44.9   763.6    53.8  761.77
    71.8  758.54    80.8  756.65    90.6  754.42   100.3  751.16   110.1   747.2
   117.9  744.46   119.9  743.76   129.6  742.49   139.4  743.75   149.2  745.76
   168.7  749.57   178.5   751.9   188.3   755.7     198  761.35   207.8  767.76
   217.6  774.56   227.4  781.57   237.1  788.62   246.9  795.56   256.7  802.24
   266.4  808.66   276.2  815.31     286  822.28   295.8  829.46
#Mann= 3 , 0 , 0
       0      .1       0   117.9    .045       0   139.4      .1       0
Bank Sta=117.9,139.4
XS Rating Curve= 0 ,0
Exp/Cntr=0.3,0.1

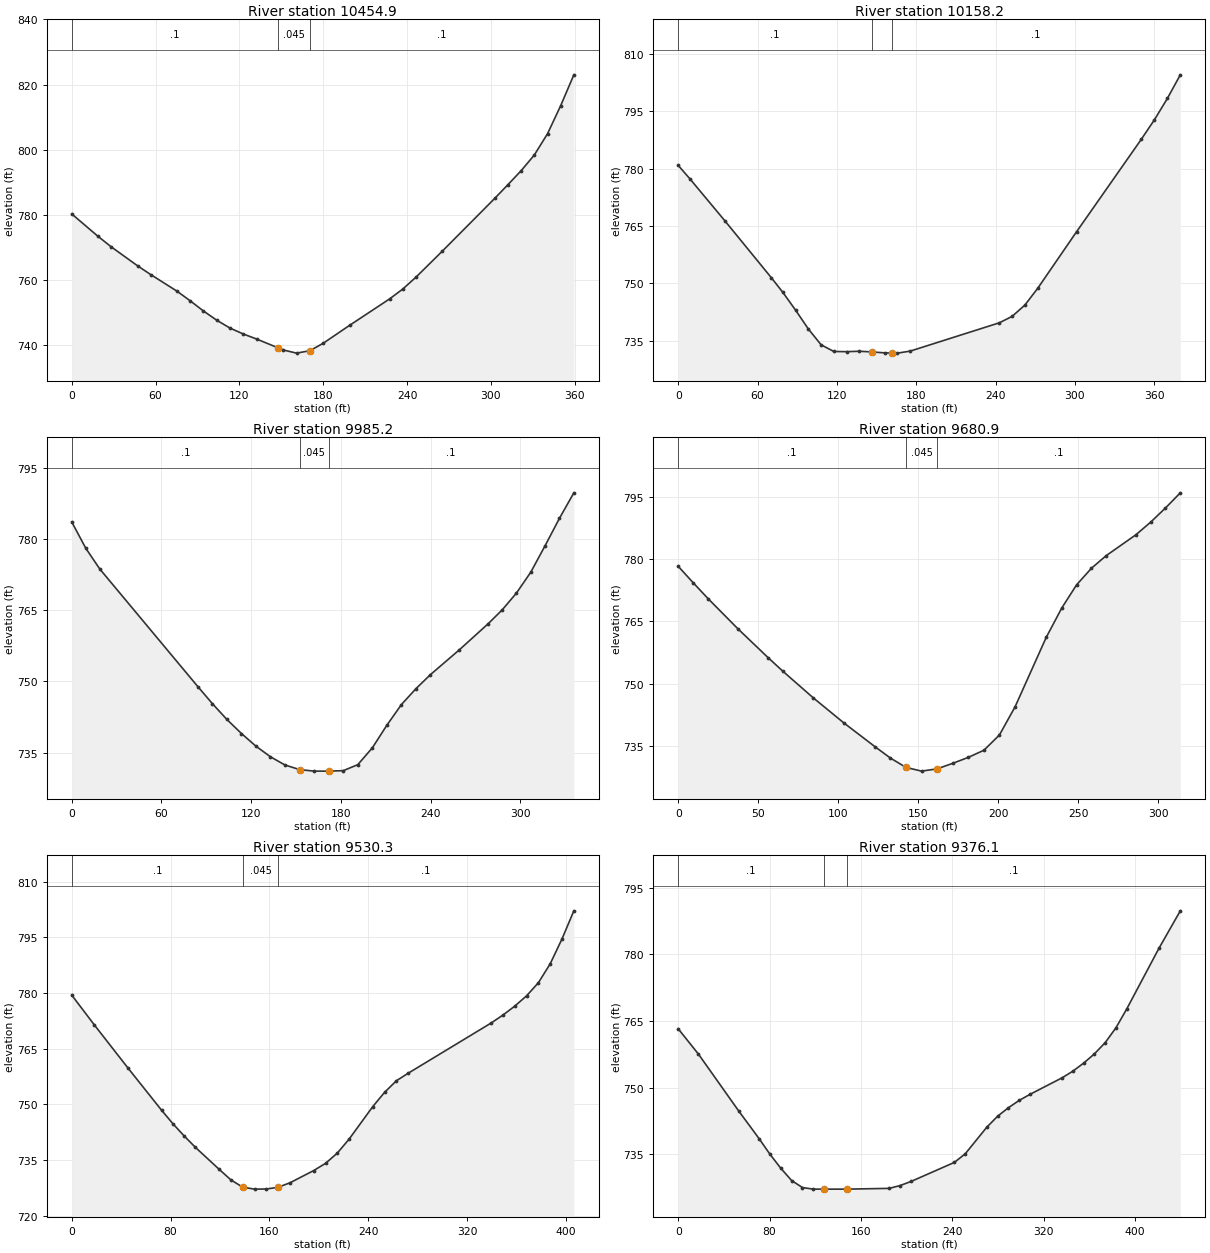
Type RM Length L Ch R = 1 ,10454.9 ,305.4,296.7,288
XS GIS Cut Line= 4
     1659825.067      749951.637     1659833.748      750045.387
     1659858.054      750166.915     1659884.095      750305.804
#Sta/Elev= 29
       0   780.2    18.8  773.31    28.2   770.1    47.1  764.25    56.5  761.56
    75.3  756.46    84.7  753.51    94.2  750.38   103.7  747.54   113.2  745.12
   122.8  743.28   132.3  741.74   147.6  739.04   151.4  738.37   160.9   737.4
   170.4  738.13     180  740.44     199  745.98   227.5  754.07   236.9  757.09
   246.4  760.76   265.2  768.74   302.9  785.04   312.3  789.24   321.7  793.51
   331.1  798.32   340.6   804.9     350  813.52   359.4  822.98
#Mann= 3 , 0 , 0
       0      .1       0   147.6    .045       0   170.4      .1       0
Bank Sta=147.6,170.4
XS Rating Curve= 0 ,0
Exp/Cntr=0.3,0.1

Type RM Length L Ch R = 1 ,10158.2 ,179.8,173,166
XS GIS Cut Line= 4
     1659474.373      750054.068     1659522.984      750116.568
     1659623.679      750269.346     1659667.081      750378.721
#Sta/Elev= 25
       0  780.82     8.8  777.33    35.2  766.39    70.4  751.51    79.2  747.64
    88.8  743.01    98.4  738.12   108.1  733.97   117.7  732.23   127.3  732.18
     137  732.29   146.6  732.11   156.2  731.87   161.8  731.83   165.8   731.8
   175.5  732.33   242.9  739.72   252.5  741.38   262.2  744.34     272  748.76
   301.4  763.54   350.4   787.7   360.2  792.73     370  798.31   379.8  804.48
#Mann= 3 , 0 , 0
       0      .1       0   146.6    .045       0   161.8      .1       0
Bank Sta=146.6,161.8
XS Rating Curve= 0 ,0
Exp/Cntr=0.3,0.1

Type RM Length L Ch R = 1 ,9985.2  ,301.8,304.3,306
XS GIS Cut Line= 4
     1659311.179       750205.11     1659382.359      750250.248
     1659503.887      750347.471     1659554.234      750429.068
#Sta/Elev= 28
       0  783.58     9.4  778.03    18.7  773.69    84.3  748.91      94  745.33
   103.7     742   113.5  739.02   123.2  736.35   132.9  734.12   142.6  732.39
   152.4  731.42   162.1   731.1   171.8   731.1   181.6   731.2   191.3  732.46
     201  735.99   210.7  740.75   220.5  745.13   230.2  748.47   239.9  751.43
   259.1  756.62   278.3  762.09   287.9  765.07   297.4   768.6     307  773.01
   316.6   778.6   326.2  784.37   335.8  789.72
#Mann= 3 , 0 , 0
       0      .1       0   152.4    .045       0   171.8      .1       0
Bank Sta=152.4,171.8
XS Rating Curve= 0 ,0
Exp/Cntr=0.3,0.1

Type RM Length L Ch R = 1 ,9680.9  ,152.3,150.6,149.1
XS GIS Cut Line= 4
     1659167.081      750451.637     1659238.262      750512.401
     1659342.429      750614.832      1659399.72      750661.707
#Sta/Elev= 27
       0  778.26     9.4  774.28    18.7  770.45    37.4  763.16    56.2  756.23
    65.5  752.93    84.2  746.61   103.3  740.57   122.8  734.82   132.6  732.03
   142.3  729.79     152  728.89   161.8  729.44   171.5  730.77   181.2   732.2
     191  733.93   200.7  737.61   210.5  744.43   229.9  761.12   239.7  768.26
   248.9   773.8   258.2  777.81   267.4  780.84     286  785.88   295.2  788.92
   304.4  792.31   313.7  795.98
#Mann= 3 , 0 , 0
       0      .1       0   142.3    .045       0   161.8      .1       0
Bank Sta=142.3,161.8
XS Rating Curve= 0 ,0
Exp/Cntr=0.3,0.1

Type RM Length L Ch R = 1 ,9530.3  ,148,154.2,160.4
XS GIS Cut Line= 3
     1659082.446      750536.707     1659132.359      750623.512
     1659364.564      750823.165
#Sta/Elev= 30
       0  779.38    18.2  771.39    45.5  759.74    72.8  748.33    81.9  744.72
      91  741.43   100.1  738.36   119.3  732.45   128.8   729.6   138.4  727.63
     148  727.11   157.6  727.14   167.1  727.62   176.7  728.83   195.8  732.11
   205.4  734.05     215  736.84   224.5  740.59   243.7  749.37   253.2  753.19
   262.8  756.32   272.4  758.36   339.4  771.86     349  774.01   358.5   776.4
   368.1  779.18   377.7  782.72   387.2  787.79   396.8  794.51   406.4   802.1
#Mann= 3 , 0 , 0
       0      .1       0   138.4    .045       0   167.1      .1       0
Bank Sta=138.4,167.1
XS Rating Curve= 0 ,0
Exp/Cntr=0.3,0.1

Type RM Length L Ch R = 1 ,9376.1  ,171.8,182.5,193.2
XS GIS Cut Line= 4
     1658989.998       750611.36     1659003.887      750680.804
     1659120.206      750854.415     1659193.123      750996.776
#Sta/Elev= 30
       0  763.24    17.7  757.54    53.1  744.67    70.8  738.49    80.3  734.98
    89.8  731.81    99.3  729.04   108.8  727.45   118.3   727.1   127.8   727.1
   147.9   727.1   184.8  727.27   194.3  727.91   203.8  728.82   241.8  733.12
   251.3  735.05   270.3  741.08   279.8  743.56   289.2  745.46   298.6   747.1
     308  748.46   336.2   752.2   345.7  753.71   355.1  755.52   364.5   757.6
   373.9  760.12   383.3  763.46   392.7  767.68   420.9  781.35   439.7  789.84
#Mann= 3 , 0 , 0
       0      .1       0   127.8    .045       0   147.9      .1       0
Bank Sta=127.8,147.9
XS Rating Curve= 0 ,0
Exp/Cntr=0.3,0.1

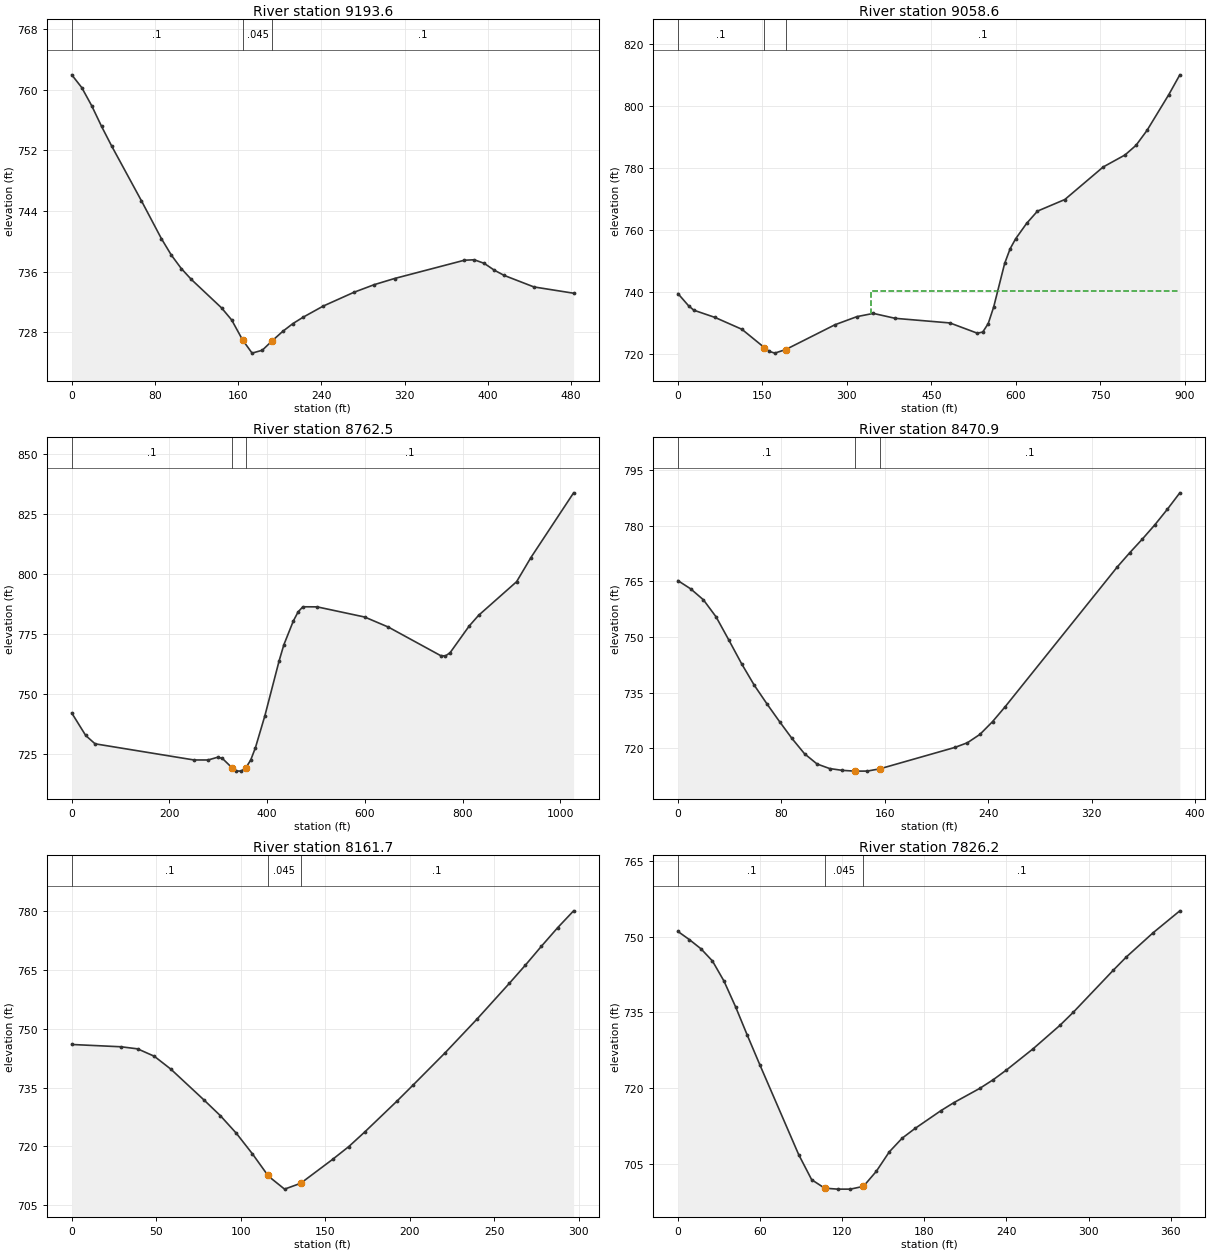
Type RM Length L Ch R = 1 ,9193.6  ,126,134.9,144.4
XS GIS Cut Line= 4
     1658884.095      750632.193     1658866.734      750755.457
     1658889.304      750949.901     1658906.665       751111.36
#Sta/Elev= 30
       0  761.97     9.6  760.29    19.2  757.89    28.7  755.16    38.3   752.6
      67  745.36    86.2  740.37    95.8  738.19   105.3  736.43   114.9     735
   144.1  731.23   153.8  729.64   164.2  727.03   173.4  725.27   183.2  725.65
     193  726.93   202.8  728.13   212.6  729.16   222.4     730   241.9  731.48
   271.3  733.29   290.9   734.3   310.4  735.11   377.5  737.52   387.1  737.58
   396.6  737.11   406.2  736.22   415.8  735.52   444.4     734   482.6  733.17
#Mann= 3 , 0 , 0
       0      .1       0   164.2    .045       0     193      .1       0
Bank Sta=164.2,193
XS Rating Curve= 0 ,0
Exp/Cntr=0.3,0.1

Type RM Length L Ch R = 1 ,9058.6  ,274.3,296.1,317.4
XS GIS Cut Line= 4
     1658811.179      750692.957     1658753.887       750767.61
     1658720.901      750939.485      1658649.72       751557.54
#Sta/Elev= 30
       0   739.5    18.8  735.58    28.2  734.15    65.9  731.81   113.6  727.99
   153.5  722.09   162.2  720.88   171.9  720.31   191.3  721.46   278.8  729.46
   317.7  732.07   346.9  733.12   385.8  731.53     483  730.04   531.6  726.74
   541.3  727.11     551  729.83   560.7  735.19   580.2  749.24   589.9  753.96
   599.6  757.15   619.1  762.12   638.5   766.1   687.1  769.84   755.2  780.33
     794  784.21   813.5  787.31   832.9  792.09   871.8  803.69   891.3  810.04
#Mann= 3 , 0 , 0
       0      .1       0   153.5    .045       0   191.3      .1       0
#XS Ineff= 2 , 0
                          343.67          740.41
Permanent Ineff=
       F       F
Bank Sta=153.5,191.3
XS Rating Curve= 0 ,0
Exp/Cntr=0.3,0.1

Type RM Length L Ch R = 1 ,8762.5  ,290.1,291.6,293.1
XS GIS Cut Line= 4
     1658807.706      750670.387     1658707.012      750699.901
     1658443.123      750795.387     1658104.581      751340.526
#Sta/Elev= 30
       0  742.01    28.6  732.62    47.7  729.15   250.1  722.41   279.1   722.4
   298.5  723.54   308.2  723.08   327.5  719.26   337.2  717.82   346.9  717.75
   356.5  719.21   366.2  722.33   375.9  727.48   395.3  740.85   424.5   763.8
   434.2  770.51   453.6  780.43   463.4  784.22   473.1  786.34   502.2  786.31
   599.5  782.07   648.1  777.87     755  765.97   764.8   765.8   774.5  767.18
   813.4  778.28   832.8  782.77   910.6  796.81   939.8  806.86  1027.3   833.9
#Mann= 3 , 0 , 0
       0      .1       0   327.5    .045       0   356.5      .1       0
Bank Sta=327.5,356.5
XS Rating Curve= 0 ,0
Exp/Cntr=0.3,0.1

Type RM Length L Ch R = 1 ,8470.9  ,322.4,309.2,296
XS GIS Cut Line= 4
     1658708.748      750468.998     1658651.456      750507.193
     1658474.373       750557.54     1658340.692      750578.373
#Sta/Elev= 28
       0  765.17     9.8  762.97    19.7     760    29.5   755.4    39.4  749.13
    49.2  742.79      59     737    68.9  731.93    78.6  727.17    88.2  722.64
    97.9  718.52   107.6  715.76   117.3  714.54     127  714.05   136.7  713.84
   146.4  713.85   156.1  714.46   214.2  720.23   223.9  721.49   233.6  723.75
   243.3  727.17     253  731.16   339.9   768.9   349.6  772.75   359.3  776.41
   368.9  780.23   378.6  784.43   388.2  788.84
#Mann= 3 , 0 , 0
       0      .1       0   136.7    .045       0   156.1      .1       0
Bank Sta=136.7,156.1
XS Rating Curve= 0 ,0
Exp/Cntr=0.3,0.1

Type RM Length L Ch R = 1 ,8161.7  ,338.8,335.5,332.1
XS GIS Cut Line= 4
     1658455.276       750236.36     1658401.456      750305.804
     1658332.012      750383.929     1658276.456      750472.471
#Sta/Elev= 25
       0  745.95    29.3  745.36      39  744.83    48.8  742.96    58.6  739.68
    78.1  731.88    87.9  727.84    97.4  723.34   106.9  718.11     116  712.66
   116.4  712.42   125.9  709.14   135.4  710.62   154.4  716.74   163.9  719.97
   173.4  723.71   192.4  731.54   201.9  735.61   220.9  743.84   239.9  752.48
   258.9  761.52   268.4  766.15   277.9  770.97   287.4  775.64   296.9  779.96
#Mann= 3 , 0 , 0
       0      .1       0     116    .045       0   135.4      .1       0
Bank Sta=116,135.4
XS Rating Curve= 0 ,0
Exp/Cntr=0.3,0.1

Type RM Length L Ch R = 1 ,7826.2  ,184.7,170,155.2
XS GIS Cut Line= 4
     1658196.595      750019.346     1658163.609       750057.54
     1658073.331      750201.637     1658062.915      750347.471
#Sta/Elev= 30
       0  751.05     8.4  749.42    16.8  747.62    25.2   745.2    33.6  741.23
    42.1  736.12    50.5  730.59    59.9  724.58    88.2  706.84    97.7  701.86
   107.2  700.19   116.6     700     126     700   135.5  700.55   144.9  703.52
   154.4  707.38   163.8  710.09   173.3  712.04   192.2  715.56   201.6  717.14
   220.5  719.96   230.3  721.67     240   723.6   259.5  727.81     279  732.43
   288.7     735     318  743.35   327.7  746.02   347.2   750.8   366.7  755.14
#Mann= 3 , 0 , 0
       0      .1       0   107.2    .045       0   135.5      .1       0
Bank Sta=107.2,135.5
XS Rating Curve= 0 ,0
Exp/Cntr=0.3,0.1

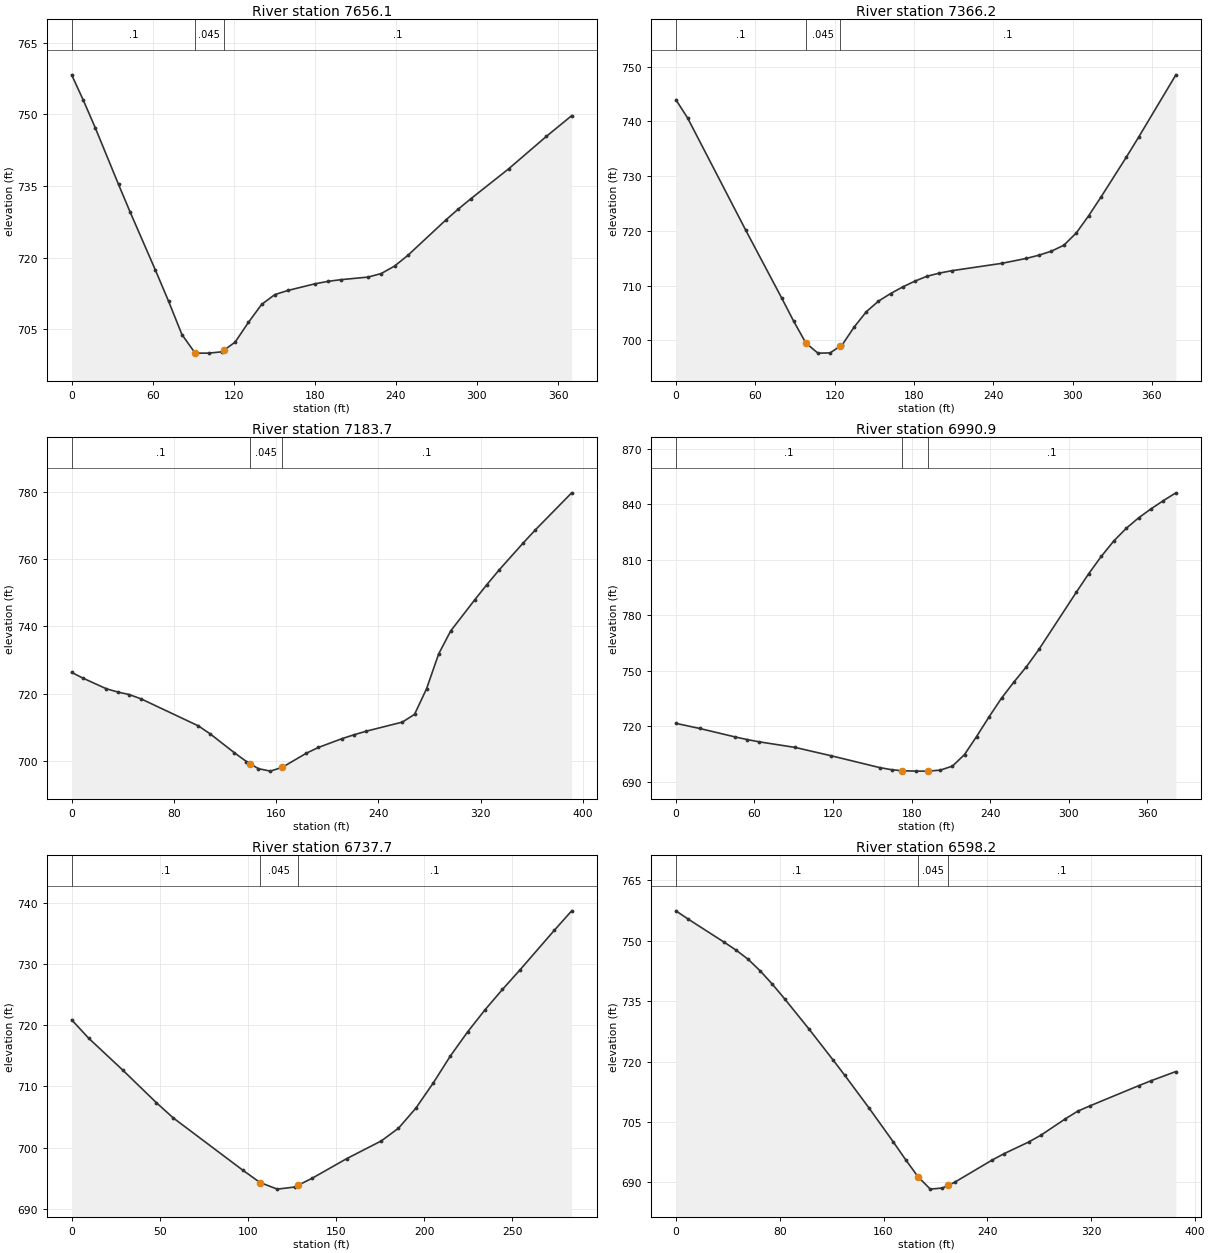
Type RM Length L Ch R = 1 ,7656.1  ,299.5,289.9,280.3
XS GIS Cut Line= 4
      1657953.54      749979.415     1657955.276      750031.498
     1657969.165      750227.679     1657996.942      750345.735
#Sta/Elev= 30
       0  758.27     8.7   752.9    17.4  747.23    34.7  735.31    43.4  729.46
      62  717.37    71.8  710.82    81.6   703.9    91.4     700   101.3     700
   111.1  700.27   112.5  700.56     121  702.31   130.8  706.42   140.6   710.2
   150.4  712.26   160.3  713.14     180  714.51   189.8  715.03   199.6  715.39
   219.3  715.92   229.1  716.66     239  718.23   248.8  720.46   276.8  727.84
   286.1  730.15   295.4  732.31   323.4  738.58   351.4  745.39   370.1  749.72
#Mann= 3 , 0 , 0
       0      .1       0    91.4    .045       0   112.5      .1       0
Bank Sta=91.4,112.5
XS Rating Curve= 0 ,0
Exp/Cntr=0.3,0.1

Type RM Length L Ch R = 1 ,7366.2  ,183.5,182.5,181.5
XS GIS Cut Line= 4
     1657656.231      750071.429     1657666.647      750132.193
     1657727.411       750245.04     1657767.342      750429.068
#Sta/Elev= 30
       0  743.98     8.8  740.67    52.8  720.15      80  707.75    89.1   703.5
    98.3  699.52   107.4  697.67   116.6  697.71   124.1  698.91   125.7  699.16
   134.9  702.46     144  705.23   153.2  707.17   162.4  708.56   171.5  709.76
   180.7  710.82   189.8  711.71   199.2  712.29   208.6  712.73   246.3  714.07
   265.1  714.98   274.6  715.57     284   716.3   293.4  717.39   302.8  719.63
   312.2  722.79   321.6  726.24   340.5  733.43   349.9  737.12   378.1  748.52
#Mann= 3 , 0 , 0
       0      .1       0    98.3    .045       0   124.1      .1       0
Bank Sta=98.3,124.1
XS Rating Curve= 0 ,0
Exp/Cntr=0.3,0.1

Type RM Length L Ch R = 1 ,7183.7  ,164.6,192.8,221
XS GIS Cut Line= 4
     1657509.095      750140.873      1657516.04      750239.832
     1657597.637      750376.985      1657609.79      750508.929
#Sta/Elev= 30
       0  726.35       9  724.62    27.1   721.5    36.1  720.52    45.1  719.76
    54.1  718.53    99.2  710.46   108.6  708.04   127.4  702.47   136.8  699.88
   139.8   699.2   146.1  697.77   155.5  697.03   164.9  698.18   183.7  702.36
   193.1  704.06   211.8  706.71   221.2  707.85   230.6   708.9   258.8  711.59
   268.3  713.89   277.7  721.46   287.2  731.84   296.6  738.66   315.6  747.99
     325  752.45   334.5  756.77   353.4  764.81   362.9  768.69   391.3  779.68
#Mann= 3 , 0 , 0
       0      .1       0   139.8    .045       0   164.9      .1       0
Bank Sta=139.8,164.9
XS Rating Curve= 0 ,0
Exp/Cntr=0.3,0.1

Type RM Length L Ch R = 1 ,6990.9  ,250.4,253.2,256
XS GIS Cut Line= 4
     1657455.276      750168.651      1657430.97      750246.776
     1657335.484      750359.623      1657266.04       750495.04
#Sta/Elev= 30
       0   721.6    18.2  718.84    45.4  714.24    54.6  712.83    63.6  711.63
    91.1   708.6   118.8  704.06   155.7   697.7     165  696.54   172.8  696.01
   183.4   695.8   192.7   695.8   201.9  696.34   211.2  698.52   220.4  704.75
   229.6  714.48   239.2  725.17   248.7  735.26   258.2  743.98   267.7  752.22
   277.2  761.52   305.7  792.35   315.2   802.4   324.8  811.75   334.3  820.02
   343.8  826.88   353.3  832.56   362.8  837.44   372.3  841.91   381.8   846.1
#Mann= 3 , 0 , 0
       0      .1       0   172.8    .045       0   192.7      .1       0
Bank Sta=172.8,192.7
XS Rating Curve= 0 ,0
Exp/Cntr=0.3,0.1

Type RM Length L Ch R = 1 ,6737.7  ,140.9,139.6,138.2
XS GIS Cut Line= 3
     1657302.498      750074.901     1657246.942      750090.526
     1657080.276      750243.304
#Sta/Elev= 23
       0  720.87     9.6  717.88    28.9  712.69    48.1  707.34    57.7  704.85
      97  696.36   106.9  694.32   116.7  693.24   126.5  693.58   128.5  693.87
   136.4     695     156   698.2   175.7   701.1   185.5  703.18   195.3  706.43
   205.2  710.55     215  714.99   224.8  718.92   234.6   722.5   244.5  725.82
   254.3  728.96     274  735.49   283.8  738.65
#Mann= 3 , 0 , 0
       0      .1       0   106.9    .045       0   128.5      .1       0
Bank Sta=106.9,128.5
XS Rating Curve= 0 ,0
Exp/Cntr=0.3,0.1

Type RM Length L Ch R = 1 ,6598.2  ,409.2,388.9,368.8
XS GIS Cut Line= 3
     1657255.189      749876.985     1657146.248      749991.568
     1656988.262      750154.762
#Sta/Elev= 29
       0  757.39     9.3  755.38    37.2  749.61    46.5  747.62    55.8  745.34
    65.1  742.45    74.4  739.16    83.7  735.59   102.3  728.17   120.9  720.47
   130.2  716.55   148.8  708.47   167.6  700.01     177  695.65   186.5  691.44
     196  688.34   205.4  688.62   209.5  689.25   214.9  690.07   243.3  695.49
   252.8  697.13   271.7  700.02   281.1   701.7   300.1  705.79   309.5  707.67
     319     709   356.8  714.04   366.3  715.26   385.2  717.52
#Mann= 3 , 0 , 0
       0      .1       0   186.5    .045       0   209.5      .1       0
Bank Sta=186.5,209.5
XS Rating Curve= 0 ,0
Exp/Cntr=0.3,0.1

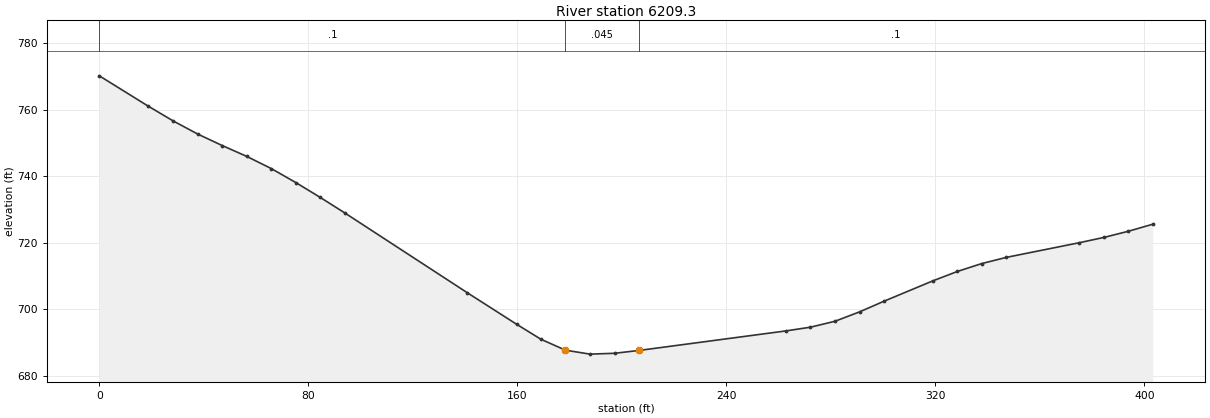
Type RM Length L Ch R = 1 ,6209.3  ,6200.7,6209.3,6216.8
XS GIS Cut Line= 4
     1656755.076      749859.702     1656771.352      749999.676
     1656785.458       750139.65      1656813.67      750257.923
#Sta/Elev= 30
       0  770.25    18.8  761.09    28.2  756.72    37.6  752.76      47   749.3
    56.4  746.03    65.8  742.37    75.2  738.16    84.6  733.67    93.9  729.05
   140.9     705   159.7  695.56     169  691.05   178.4  687.76   187.8  686.57
   197.2  686.82   206.6  687.68   262.8  693.55   272.2  694.67   281.6  696.46
     291  699.28   300.3  702.47     319  708.59   328.4  711.42   337.7  713.79
   347.1  715.65   375.1  720.07   384.5  721.66   393.8   723.5   403.2  725.63
#Mann= 3 , 0 , 0
       0      .1       0   178.4    .045       0   206.6      .1       0
Bank Sta=178.4,206.6
XS Rating Curve= 0 ,0
Exp/Cntr=0.3,0.1

Chan Stop Cuts=-1
Use User Specified Reach Order=0
Composite Channel Slope=5